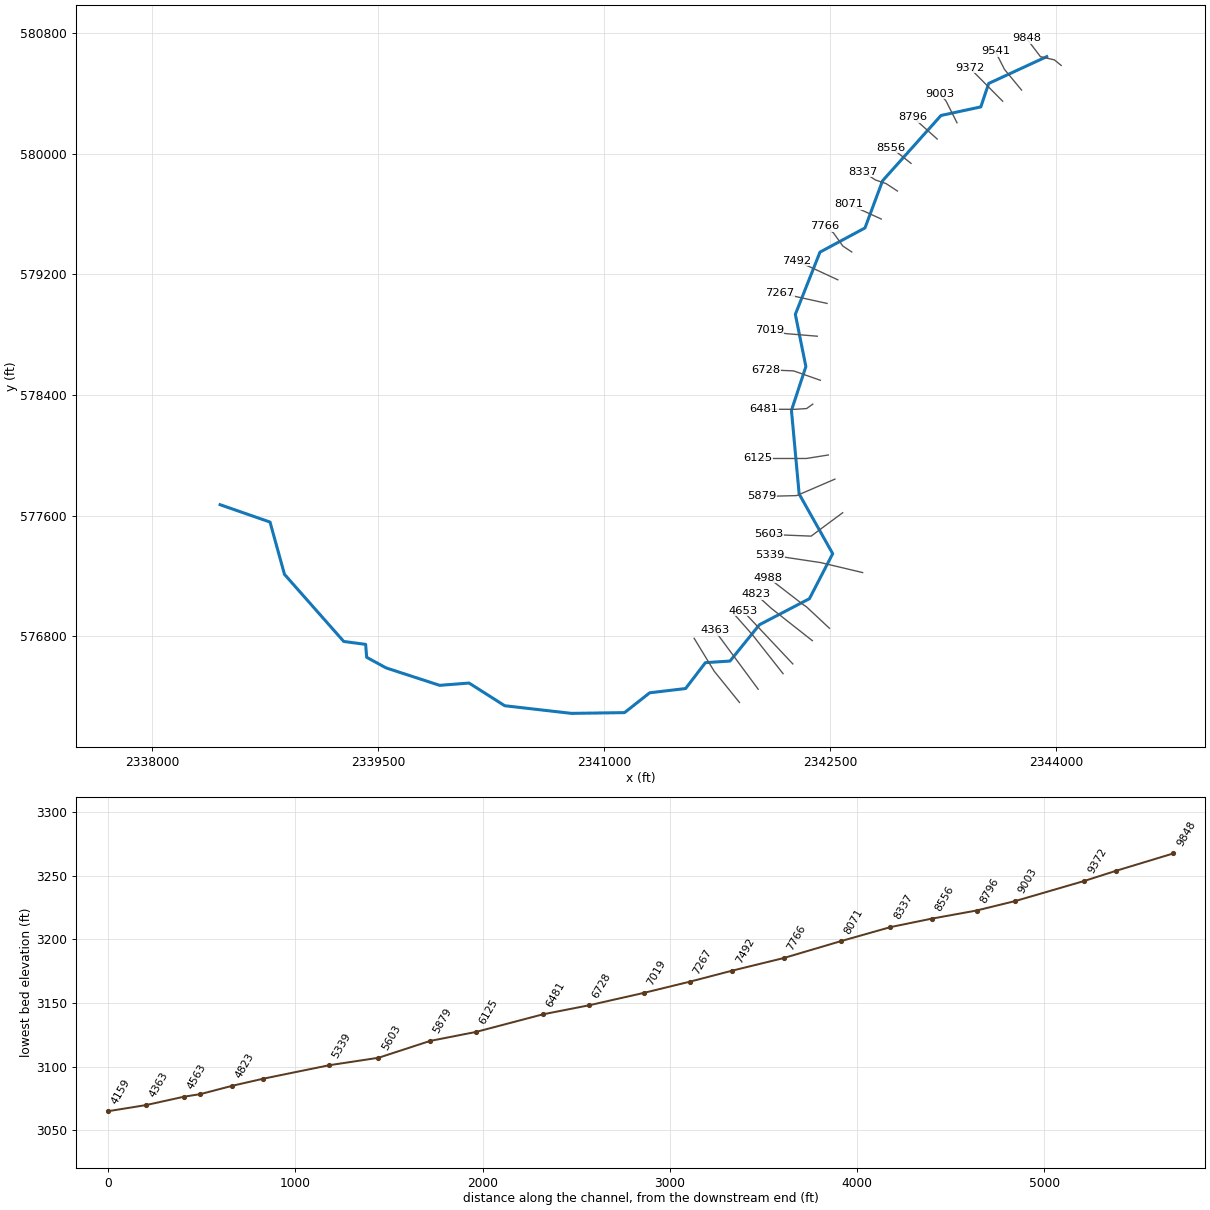
--- POCARN.prj (project) ---

Proj Title=POCARN
Current Plan=p01
Default Exp/Contr=0,0
English Units
Geom File=g01
Flow File=f01
Plan File=p01
Background Map Layer=Inundation Boundary (01pct Value_0)
Background Map Layer=Inundation Boundary (01pct Value_0)
BEGIN DESCRIPTION:
----------MODEL BY WOOD PLC 2021----------
Stream Name: Poca Run
Flood Zone: Enhanced Approximate
Pocahontas County, WV
HEC-RAS Version: RAS 6.1
Vertical Datum: NAVD88
Projection: NAD 1983 StatePlane West Virginia S FIPS 4702 (US Feet)
Terrain: 1-meter LIDAR (FEMA Region III 3DEP collected 2016-2018)
Land Use: 2019 NLCD
Hydrologic Method:
WV SIR2010-5033 regression equations
Model Notes:
Normal depth tie in with Eastfork Greenbrier river
END DESCRIPTION:
DSS Export Rating Curves= 0
DSS Export Rating Curve Sorted= 0
DSS Export Volume Flow Curves= 0
DXF OffsetX= 0
DXF OffsetY= 0
DXF ScaleX= 0
DXF ScaleY= 0

--- POCARN.p01 (plan) ---

Plan Title=Floodplain
Program Version=6.10
Short Identifier=Floodplain
Geom File=g01
Flow File=f01
Subcritical Flow
K Sum by GR= 0
Std Step Tol= 0.01
Critical Tol= 0.01
Num of Std Step Trials= 20
Max Error Tol= 0.3
Flow Tol Ratio= 0.001
Split Flow NTrial= 30
Split Flow Tol= 0.02
Split Flow Ratio= 0.02
Log Output Level= 0
Friction Slope Method= 1
Unsteady Friction Slope Method= 2
Unsteady Bridges Friction Slope Method= 1
Parabolic Critical Depth
Global Vel Dist= 0 , 0 , 0
Global Log Level= 0
CheckData=True
Encroach Param=-1 ,0,0, 0
Mapping Interval=1HOUR
Computation Time Step Use Courant=        0
Computation Time Step Use Time Series=    0
Computation Time Step Count To Double=0
Computation Time Step Max Doubling=0
Computation Time Step Max Halving=0
Computation Time Step Residence Courant=0
Run HTab= 0
Run UNet= 0
Run Sediment= 0
Run PostProcess= 0
Run WQNet= 0
Run RASMapper=-1
UNET Theta= 0
UNET Theta Warmup= 0
UNET ZTol= 0
UNET ZSATol= 0
UNET MxIter= 0
UNET Max Iter WO Improvement= 0
UNET MaxInSteps= 0
UNET DtIC= 0
UNET DtMin= 0
UNET MaxCRTS= 0
UNET WFStab= 0
UNET SFStab= 0
UNET WFX= 1
UNET SFX= 1
UNET Gravity=32.174
UNET 1D Methodology=Finite Difference
UNET DSS MLevel= 1
UNET Pardiso=0
UNET DZMax Abort= 0
UNET Use Existing IB Tables= 0
UNET Froude Reduction=False
UNET Froude Limit= 0
UNET Froude Power= 0
UNET D1 Cores= 0
UNET WindReference=Eulerian
UNET WindDragFormulation=Hsu (1988)
UNET D2 Coriolis=0
UNET D2 Cores= 0
UNET D2 Theta= 1
UNET D2 Theta Warmup= 1
UNET D2 Z Tol= 0.01
UNET D2 Volume Tol= 0.01
UNET D2 Max Iterations= 20
UNET D2 Equation= 0
UNET D2 RampUpFraction=0.1
UNET D2 TimeSlices= 1
UNET D2 Turbulence Formulation=Non-Conservative (original)
UNET D2 Eddy Viscosity=0.3
UNET D2 Transverse Eddy Viscosity=0.1
UNET D2 Smagorinsky Mixing=0
UNET D2 BCVolumeCheck=0
UNET D2 Cores=0
UNET D2 SolverType=PARDISO (Direct)
UNET D2 Minimum Iterations= 2147483647
UNET D2 Maximum Iterations= 2147483647
UNET D2 Restart Number= 10
UNET D2 Relaxation Coeff=1.3
UNET D2 SOR Precondition Iterations= 10
UNET D2 ILUT Maximum Fill= 8
UNET D2 ILUT Tolerance=1E-08
UNET D1D2 MaxIter= 0
UNET D1D2 ZTol=0.01
UNET D1D2 QTol=0.1
UNET D1D2 MinQTol=1
Write IC File= 0
Write IC File at Fixed DateTime=0
Write IC File at Sim End=0
Echo Input=False
Echo Parameters=False
Echo Output=False
Write Detailed= 0
HDF Write Warmup=0
HDF Write Time Slices=0
HDF Flush=0
HDF Compression= 1
HDF Chunk Size= 1
HDF Spatial Parts= 1
HDF Use Max Rows=0
HDF Fixed Rows= 1
Calibration Method= 0
Calibration Iterations= 20
Calibration Max Change=0.05
Calibration Tolerance=0.2
Calibration Maximum=1.5
Calibration Minimum=0.5
Calibration Optimization Method= 1
WQ AD Non Conservative
WQ ULTIMATE=-1
WQ Max Comp Step=1HOUR
WQ Output Interval=15MIN
WQ Output Selected Increments= 0
WQ Output face flow=0
WQ Output face velocity=0
WQ Output face area=0
WQ Output face dispersion=0
WQ Output cell volume=0
WQ Output cell surface area=0
WQ Output cell continuity=0
WQ Output cumulative cell continuity=0
WQ Output face conc=0
WQ Output face dconc_dx=0
WQ Output face courant=0
WQ Output face peclet=0
WQ Output face adv mass=0
WQ Output face disp mass=0
WQ Output cell mass=0
WQ Output cell source sink temp=0
WQ Output nsm pathways=0
WQ Output nsm derived pathways=0
WQ Create Restart=0
WQ Fixed Restart=0
WQ System Summary=0
WQ Write To DSS=0
Sorting and Armoring Iterations= 10
XS Update Threshold= 0.02
Bed Roughness Predictor= 0
Hydraulics Update Threshold= 0.02
Energy Slope Method= 1
Volume Change Method= 1
Sediment Retention Method= 0
Sediment TS Multiplier= 1
Warm Up Method= 0
XS Weighting Method= 0
Number of US Weighted Cross Sections= 1
Number of DS Weighted Cross Sections= 1
Upstream XS Weight=0
Main XS Weight=1
Downstream XS Weight=0
Number of DS XS's Weighted with US Boundary= 1
Upstream Boundary Weight= 1
Weight of XSs Associated with US Boundary= 0
Number of US XS's Weighted with DS Boundary= 1
Downstream Boundary Weight= 0.5
Weight of XSs Associated with DS Boundary= 0.5
Percentile Method= 0
Sediment Output Level= 3
Mass or Volume Output= 0
Output Increment Type= 1
Profile and TS Output Increment= 1
Transport Output Increment 1
XS Output Flag= 0
XS Output Increment= 10
Read HDF5 Sediment Hotstart= 0
Sediment Hotstart Type= 0
Write Gradation File= 0
Read Gradation Hotstart= 0
Write HDF5 File= 1
Write Binary Output= 1
Write DSS Sediment File= 0
DSS Sediment Output Type= 1
SV Curve= 0
Specific Gage Flag= 0
Subcell Erosion Methods= 0
Subcell Deposition Methods= 0
Advection Scheme= 1
Matrix Solver= 0
Implicit Weighting Factor= 1
Maximum Outer Loop Convergence Iterations= 5
Convergence Maximum Absolute= 0.001
Convergence RMSE= 0.0001
Grain Fractions Max Abs Error= 0.001
Max Subgrid Regions= 1
Max Subgrid Length Scale= 3.402823E+38
Initial Layer Thickness= 3.402823E+38
Min Layer Thickness= 3.402823E+38
Max Layer Thickness= 3.402823E+38
Number of Layers= 5

--- POCARN.f01 (steady flow) ---

Flow Title=Flow
Program Version=6.10
Number of Profiles= 6
Profile Names=01pct,10pct,04pct,02pct,0_2pct,01plus
River Rch & RM=POCARN,Main            ,9848
     860     462     609     731    1190    1270
River Rch & RM=POCARN,Main            ,3476
    1090     588     772     924    1500    1610
River Rch & RM=POCARN,Main            ,1466
    1480     809    1060    1260    2030    2180
Boundary for River Rch & Prof#=POCARN,Main            , 1
Up Type= 0
Dn Type= 3
Dn Slope=0.01532
Boundary for River Rch & Prof#=POCARN,Main            , 2
Up Type= 0
Dn Type= 3
Dn Slope=0.01532
Boundary for River Rch & Prof#=POCARN,Main            , 3
Up Type= 0
Dn Type= 3
Dn Slope=0.01532
Boundary for River Rch & Prof#=POCARN,Main            , 4
Up Type= 0
Dn Type= 3
Dn Slope=0.01532
Boundary for River Rch & Prof#=POCARN,Main            , 5
Up Type= 0
Dn Type= 3
Dn Slope=0.01532
Boundary for River Rch & Prof#=POCARN,Main            , 6
Up Type= 0
Dn Type= 3
Dn Slope=0.01532
DSS Import GetInterval= 0
DSS Import GetPeak= 0
DSS Import FillOption= 0

--- POCARN.g01 (geometry) ---

Geom Title=Geometry
Program Version=6.10

River Reach=POCARN          ,Main
Reach XY= 30
2343935.26085855580645.0507138972343550.24705345580467.142559247
2343497.85273296580311.5776700522343233.81442221580254.713213669
2342846.16625197 579821.473948972342729.45861372579508.556964666
2342430.97023197579348.1235177222342267.47024339578935.440413348
 2342337.3585642578588.9831388942342241.71043989578298.060657233
2342292.69524606577743.5893252342342515.33104566577347.511753862
 2342361.0093923577048.9200490962342029.15176084576875.940364033
2341834.17847045 576635.319442482341670.78244789576624.471812814
 2341539.4773269576452.8473909792341301.28983711576424.590564107
2341134.27325058576292.9870459532340781.79655586576288.038910683
2340339.53979536576338.7496245152340102.73587901576489.168891232
2339907.61654718576474.0914883182339552.37612256576589.731660274
2339423.51214603576660.0116040162339416.89790106576745.884239517
2339271.50592828576765.1096243472338878.41308515577210.151466411
2338782.28616101 577557.276470282338451.31158015577672.435907369

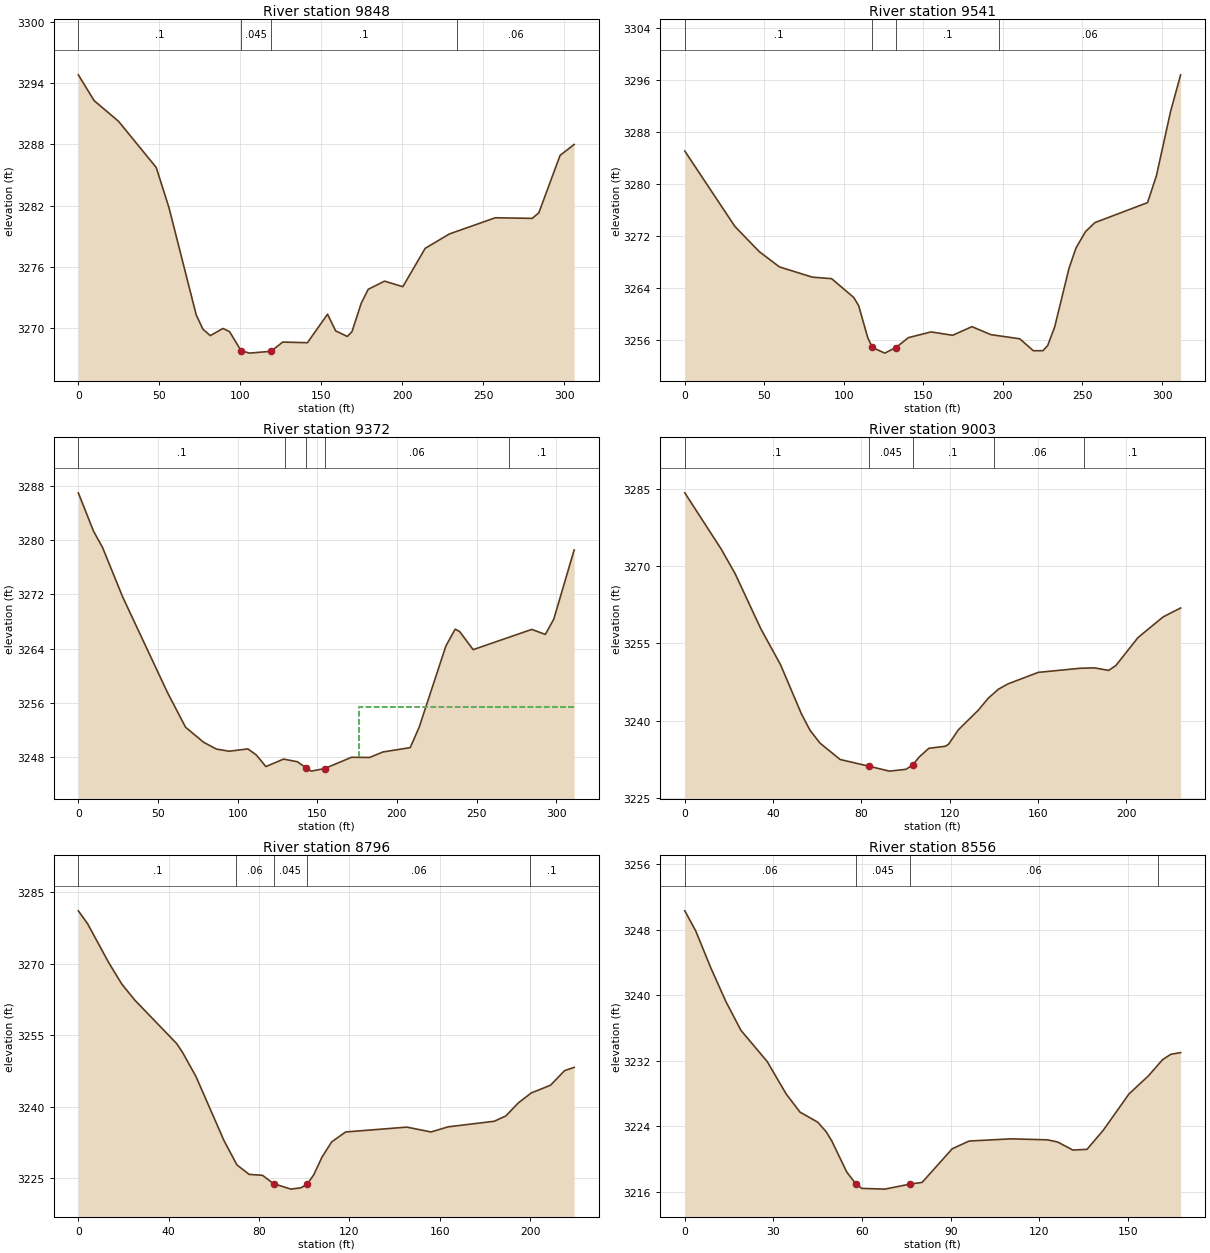
Type RM Length L Ch R = 1 ,9848    ,306.4,306.4,306.4
XS GIS Cut Line= 4
2344031.32963028580586.5258037692343986.46685597580623.565736442
2343893.49036082580644.909740491 2343801.2727836580766.493447555
#Sta/Elev= 30
       0 3294.81     9.8 3292.28    24.8 3290.27    48.1 3285.75      56 3281.81
    72.8 3271.33    76.9 3269.94    81.5  3269.3    89.3    3270    93.4 3269.69
100.52753267.822   105.7 3267.59     119 3267.77   126.2 3268.67   141.5 3268.61
   153.9  3271.4   158.9 3269.77   166.1 3269.22     169 3269.69   174.7 3272.47
     179 3273.83   189.1 3274.63   200.4 3274.09   214.2 3277.84   229.2 3279.25
   257.5 3280.83   280.3 3280.77   284.4 3281.32   297.5 3286.93   306.2    3288
#Mann= 4 ,-1,0
       0      .1       0100.5275    .045       0     119      .1       0
  233.57     .06       0
Bank Sta=100.5275,119
XS Rating Curve= 0 ,0
Exp/Cntr=0.3,0.1

Type RM Length L Ch R = 1 ,9541    ,167.5,168.9,168.8
XS GIS Cut Line= 3
2343768.24379138580423.3141792782343655.15436969580560.211900282
2343594.26006569580679.711248717
#Sta/Elev= 30
       0 3285.08    31.5 3273.46    46.8 3269.58    59.5 3267.22    80.2 3265.64
    92.3 3265.41   106.2 3262.51   109.3 3261.25     115 3256.32   117.9  3254.8
   125.7 3253.93   132.7 3254.79   140.6 3256.32   154.8  3257.2   168.4 3256.68
   180.5 3258.01   192.4 3256.78   210.6 3256.14   219.1  3254.3   225.1  3254.3
   228.1 3255.08   232.5 3257.94   241.5 3266.97   245.9 3270.13   251.9 3272.66
   257.8 3274.05   290.9 3277.13   296.5 3281.29   305.4 3291.19   311.7 3296.83
#Mann= 4 ,-1,0
       0      .1       0   117.9    .045       0   132.7      .1       0
  197.57     .06       0
Bank Sta=117.9,132.7
XS Rating Curve= 0 ,0
Exp/Cntr(USF)=0,0
Exp/Cntr=0.3,0.1

Type RM Length L Ch R = 1 ,9372    ,371.2,369,364.4
XS GIS Cut Line= 2
2343642.88393851 580349.416881052343423.66444414580570.284642296
#Sta/Elev= 30
       0 3286.93     9.5 3281.31    15.2 3278.89    27.8 3271.63      56 3257.53
    67.3 3252.45    78.6 3250.24    86.6 3249.24    94.7 3248.92   106.4 3249.26
   111.7 3248.37   117.7 3246.66   128.8 3247.76   137.5 3247.37   143.2 3246.43
   146.2 3245.99   154.5 3246.36   171.5 3248.03   182.8    3248   191.2 3248.81
   208.3 3249.45   213.9 3252.44   230.7 3264.41   236.5 3266.87   239.3 3266.53
   247.8 3263.86   284.6 3266.84   293.1  3266.1   298.4 3268.35311.1909 3278.53
#Mann= 5 ,-1,0
       0      .1       0     130     .06       0   143.2    .045       0
   154.5     .06       0     270      .1       0
#XS Ineff= 2 , 0
                          176.16         3255.49
Permanent Ineff=
       F       F
Bank Sta=143.2,154.5
XS Rating Curve= 0 ,0
Exp/Cntr(USF)=0,0
Exp/Cntr=0.3,0.1

Type RM Length L Ch R = 1 ,9003    ,201.3,207,211.7
XS GIS Cut Line= 3
2343340.01490023580206.4297296472343267.49115773580350.241014488
2343227.93275273580400.101087456
#Sta/Elev= 30
       0 3284.21    16.5 3273.29    22.8 3268.53    34.4 3257.87    43.4 3250.84
    52.9 3241.26    56.8 3238.09    61.3 3235.62    70.4 3232.45    83.7 3231.12
    92.7 3230.19   100.2 3230.54   103.2 3231.33   106.2 3232.92   110.6 3234.62
   118.1 3235.02   119.6 3235.44     124 3238.22     133 3242.01   137.5 3244.33
   142.1 3246.08   146.4 3247.11   160.2 3249.36   179.3 3250.16   185.7 3250.23
   192.1 3249.74   195.4 3250.71   205.4 3256.12   216.8 3260.13224.7099 3261.86
#Mann= 5 ,-1,0
       0      .1       0    83.7    .045       0   103.2      .1       0
     140     .06       0  181.06      .1       0
Bank Sta=83.7,103.2
XS Rating Curve= 0 ,0
Exp/Cntr(USF)=0,0
Exp/Cntr=0.3,0.1

Type RM Length L Ch R = 1 ,8796    ,239.5,240.4,241.1
XS GIS Cut Line= 2
2343208.56561695580098.4682493372343044.97512961 580244.75193449
#Sta/Elev= 30
       0 3281.08     4.1 3278.38    13.5 3270.18    19.2 3265.76    24.9 3262.41
    43.5 3253.27    46.1 3251.43    52.1 3246.32    64.5 3232.88    70.2 3227.82
    75.6 3225.83    81.5 3225.64    86.4 3223.89    94.1 3222.74    98.5 3223.01
   101.3 3223.78   104.2 3225.75   107.8 3229.41   112.1 3232.62   118.3 3234.72
   145.4 3235.74   156.1 3234.72   163.7  3235.8   184.1 3236.97   189.2 3238.08
   194.8 3240.84   200.5 3242.91     209 3244.52   215.2 3247.58219.4556 3248.26
#Mann= 5 ,-1,0
       0      .1       0      70     .06       0    86.4    .045       0
   101.3     .06       0     200      .1       0
Bank Sta=86.4,101.3
XS Rating Curve= 0 ,0
Exp/Cntr(USF)=0,0
Exp/Cntr=0.3,0.1

Type RM Length L Ch R = 1 ,8556    ,212.5,218.9,222.2
XS GIS Cut Line= 2
2343035.08552836 579936.938095592342903.63624508580041.190975432
#Sta/Elev= 30
       0  3250.3     3.7 3247.85     8.8 3243.34    13.9 3239.23      19 3235.71
    27.9 3231.89    34.3 3227.94      39 3225.72      45 3224.49    47.8 3223.34
    49.7 3222.23    54.8 3218.41   57.79    3217    59.9 3216.41    67.7 3216.32
    76.3 3216.94    80.3 3217.14    90.5 3221.25    96.2 3222.19   110.4 3222.46
   122.7 3222.34   126.2 3222.07   131.3 3221.09   136.1 3221.18   141.6 3223.51
   150.3 3227.94   156.9 3230.16   161.7 3232.14   164.5 3232.79167.7724 3232.99
#Mann= 4 ,-1,0
       0     .06       0   57.79    .045       0    76.3     .06       0
     160      .1       0
Bank Sta=57.79,76.3
XS Rating Curve= 0 ,0
Exp/Cntr(USF)=0,0
Exp/Cntr=0.3,0.1

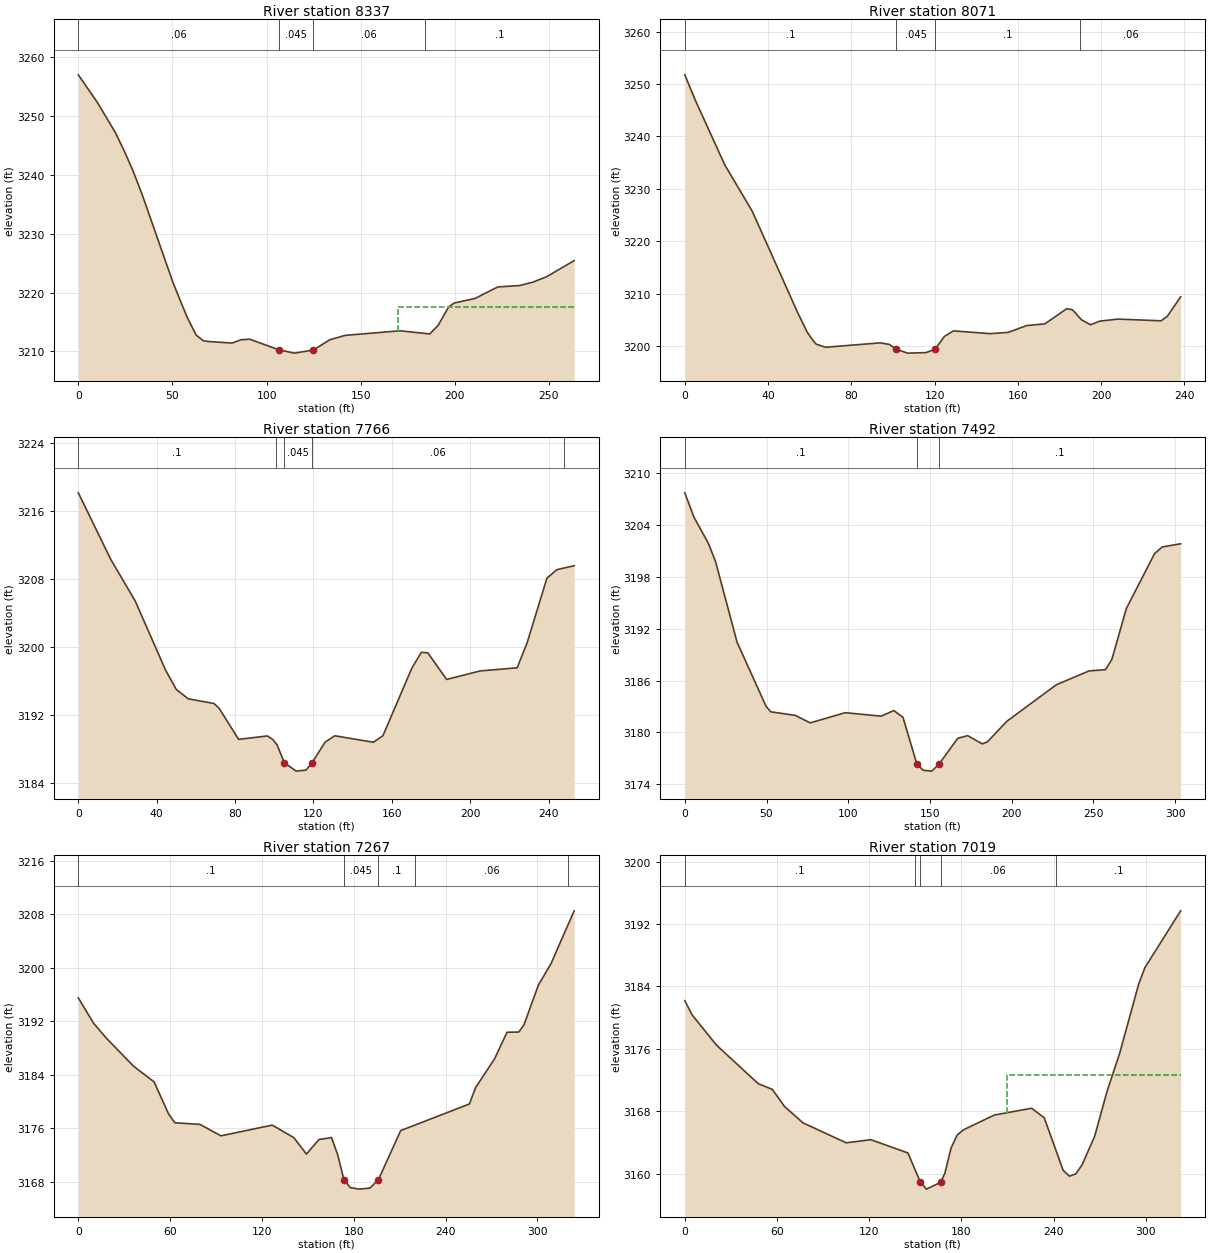
Type RM Length L Ch R = 1 ,8337    ,266.4,266.3,264.5
XS GIS Cut Line= 4
2342944.51756392579753.5396972732342869.22636099579802.885958653
 2342799.0224015579826.7960028272342716.10033341579881.229507649
#Sta/Elev= 30
       0 3257.03      10 3252.39    19.5 3247.31    24.3 3244.15    28.9 3240.82
    33.9 3236.68    50.4 3221.61    57.8 3215.82    62.6 3212.78    66.4 3211.83
    69.3 3211.69    81.7 3211.43    86.5    3212    91.1 3212.08  106.61 3210.28
   114.7 3209.72   124.9 3210.25   133.6    3212   141.8 3212.74   170.9 3213.52
   186.7 3212.98   191.1 3214.43   196.8 3217.61   199.7 3218.24   210.7 3219.01
   222.8 3220.97   234.4 3221.21   241.4 3221.78   248.7  3222.7263.3772 3225.45
#Mann= 4 ,-1,0
       0     .06       0  106.61    .045       0   124.9     .06       0
  184.19      .1       0
#XS Ineff= 2 , 0
                          169.86         3217.56
Permanent Ineff=
       F       F
Bank Sta=106.61,124.9
XS Rating Curve= 0 ,0
Exp/Cntr(USF)=0,0
Exp/Cntr=0.3,0.1

Type RM Length L Ch R = 1 ,8071    ,310.5,304.9,295.7
XS GIS Cut Line= 2
2342837.68545165579567.7422618132342620.79930628579666.265209792
#Sta/Elev= 30
       0 3251.76     5.2 3246.79    19.2 3234.57    32.4 3225.72    54.4 3206.21
    58.8 3202.63    61.5 3201.08    63.2 3200.32    67.6 3199.74    93.9 3200.58
    98.3 3200.28  101.56 3199.36   107.1 3198.62   115.9 3198.72   120.3 3199.39
   124.7  3201.8   129.1 3202.87   146.6 3202.34   155.4 3202.58   164.2 3203.88
     173 3204.21   183.5  3207.1   186.2 3206.92   190.6 3204.98     195 3204.03
   199.4 3204.73   208.1 3205.12   228.8 3204.79   231.8 3205.64 238.215 3209.37
#Mann= 4 ,-1,0
       0      .1       0  101.56    .045       0   120.3      .1       0
     190     .06       0
Bank Sta=101.56,120.3
XS Rating Curve= 0 ,0
Exp/Cntr(USF)=0,0
Exp/Cntr=0.3,0.1

Type RM Length L Ch R = 1 ,7766    ,267.2,273.8,279.6
XS GIS Cut Line= 4
2342641.82657917579349.1038436932342582.81455525579388.275618191
2342520.75018526579475.267481036  2342461.229437579521.561396352
#Sta/Elev= 30
       0 3218.12    16.4 3210.35    29.1 3205.36    44.5 3197.27      50 3194.98
    56.1 3193.88    69.2 3193.33    71.9 3192.76    81.8 3189.11    96.5 3189.51
    99.2  3189.1   101.4 3188.48  105.22 3186.34   111.2 3185.37   116.2 3185.49
   119.3 3186.35     126 3188.79   130.9 3189.53   150.6 3188.77   155.5 3189.54
   170.2 3197.47   175.1 3199.35   178.4 3199.29     188 3196.16   205.1 3197.16
     224 3197.53   229.1 3200.48   239.2 3208.08   244.3 3209.08253.0966 3209.54
#Mann= 5 ,-1,0
       0      .1       0  100.83     .06       0  105.22    .045       0
   119.3     .06       0  247.69      .1       0
Bank Sta=105.22,119.3
XS Rating Curve= 0 ,0
Exp/Cntr(USF)=0,0
Exp/Cntr=0.3,0.1

Type RM Length L Ch R = 1 ,7492    ,217.8,224.6,227.1
XS GIS Cut Line= 2
2342549.23874853579164.4369067752342274.01887836579292.126717151
#Sta/Elev= 30
       0 3207.76     5.6 3204.94    14.4 3201.92    18.8 3199.81      32 3190.45
    49.7 3183.04    52.6 3182.39    67.6 3181.98    76.7 3181.11    98.2 3182.29
   120.2 3181.89   127.9 3182.54   133.5 3181.76  141.97 3176.35   145.9 3175.62
   151.1 3175.52   155.5 3176.32     167 3179.32   173.1 3179.63     182 3178.68
   185.1  3178.9   197.1  3181.3   227.3 3185.52   247.4 3187.13   257.4 3187.27
   261.3 3188.45   270.2 3194.36   287.5 3200.73   292.2 3201.49303.3985 3201.86
#Mann= 3 ,-1,0
       0      .1       0  141.97    .045       0   155.5      .1       0
Bank Sta=141.97,155.5
XS Rating Curve= 0 ,0
Exp/Cntr(USF)=0,0
Exp/Cntr=0.3,0.1

Type RM Length L Ch R = 1 ,7267    ,246.8,248.7,250.3
XS GIS Cut Line= 2
2342477.83939151579007.8473511142342161.29979961579077.373011478
#Sta/Elev= 30
       0  3195.5     9.9 3191.73    18.1 3189.54    36.1 3185.29    49.5 3182.95
      59 3178.15    63.1 3176.83    79.5 3176.59    93.2 3174.88   126.8 3176.48
   140.9  3174.6   149.1 3172.15   157.3 3174.33   165.5 3174.62   169.6 3171.99
   173.6 3168.31   177.8 3167.13   183.8 3166.91   190.6 3167.07  196.13 3168.32
   210.7 3175.66   255.6 3179.64   259.7 3182.11     272 3186.36   280.2 3190.36
   287.9  3190.4   291.3 3191.48   300.7 3197.41   308.9  3200.6324.0851 3208.52
#Mann= 5 ,-1,0
       0      .1       0   173.6    .045       0  196.13      .1       0
     220     .06       0     320      .1       0
Bank Sta=173.6,196.13
XS Rating Curve= 0 ,0
Exp/Cntr(USF)=0,0
Exp/Cntr=0.3,0.1

Type RM Length L Ch R = 1 ,7019    ,295.1,290.6,284.8
XS GIS Cut Line= 3
2342412.83572532578790.2263816832342201.99774714578807.749109091
2342093.46988706578831.489578484
#Sta/Elev= 30
       0 3182.17     4.7 3180.36    20.7 3176.45    47.8 3171.52    56.9  3170.8
    64.9  3168.6    76.9  3166.5     105 3163.94   121.1 3164.34   145.2 3162.64
   153.2 3158.94   157.2    3158   166.4 3158.86   169.2    3160   173.3 3163.28
   177.3 3164.95   181.3  3165.6   201.4  3167.5   225.7 3168.37   233.9 3167.15
   246.2 3160.42   250.3 3159.66   254.4 3159.95   258.5  3161.1   266.7 3164.77
   274.8 3170.55     283 3175.42   295.3 3184.25   299.4  3186.4 322.659 3193.69
#Mann= 5 ,-1,0
       0      .1       0     150     .06       0   153.2    .045       0
   166.4     .06       0  241.56      .1       0
#XS Ineff= 2 , 0
                          209.61         3172.59
Permanent Ineff=
       F       F
Bank Sta=153.2,166.4
XS Rating Curve= 0 ,0
Exp/Cntr(USF)=0,0
Exp/Cntr=0.3,0.1

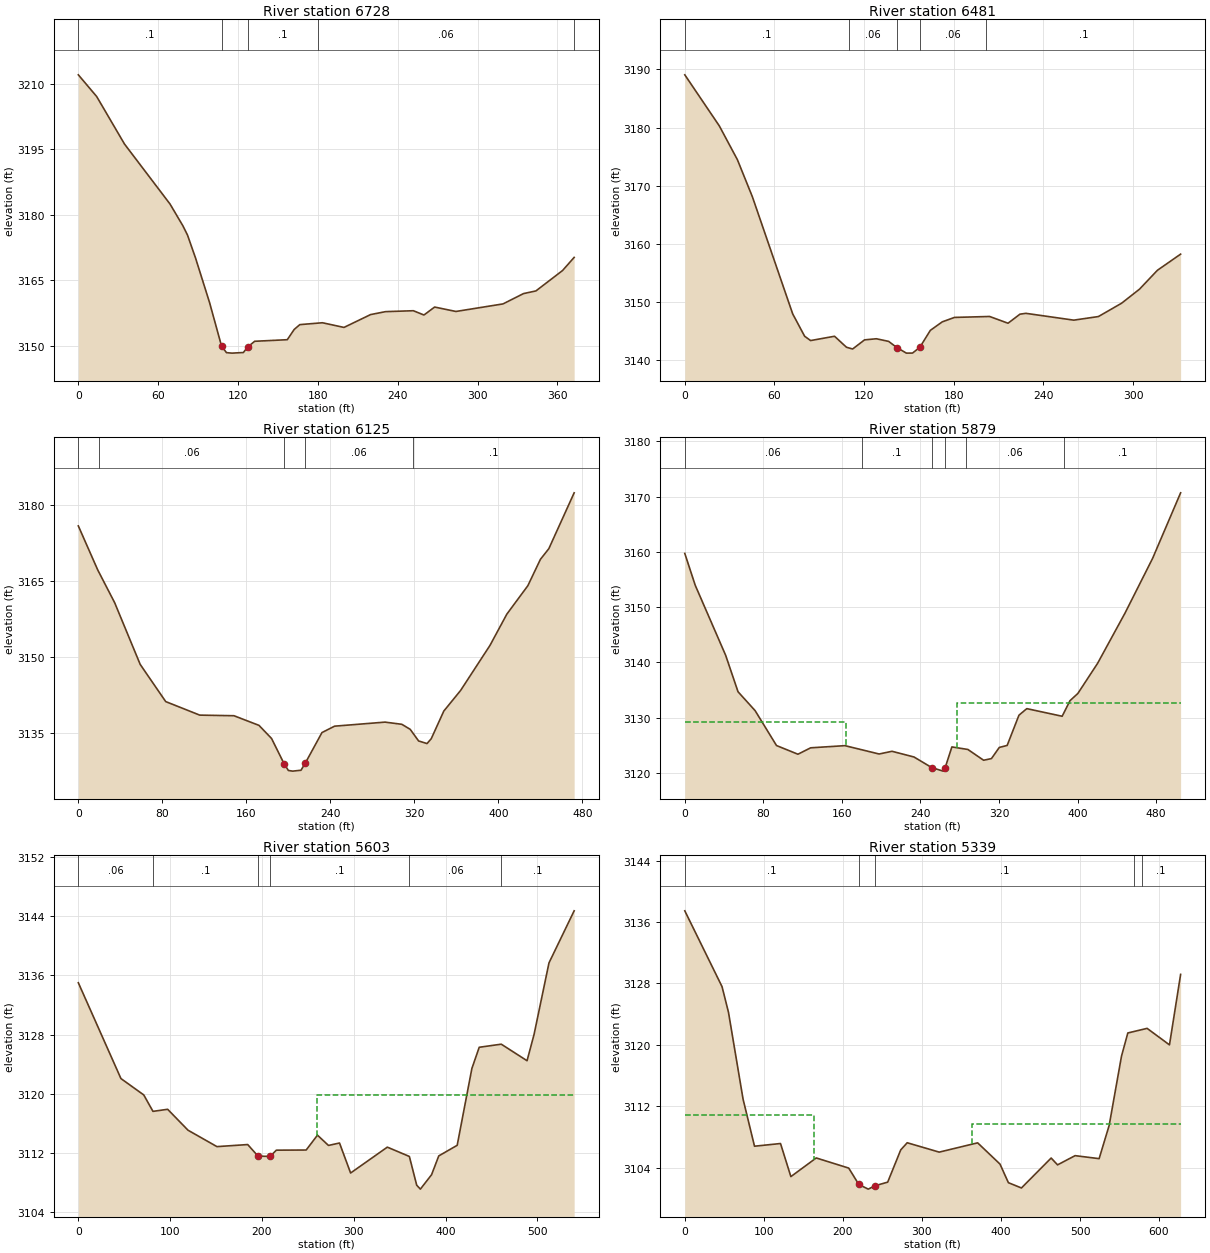
Type RM Length L Ch R = 1 ,6728    ,241.9,246.7,250.4
XS GIS Cut Line= 3
2342433.18469908578497.9925084462342256.26167718578560.169928283
2342071.42516548578568.083418081
#Sta/Elev= 30
       0 3211.99    13.8 3207.02    34.7 3196.15    68.9 3182.43    78.6 3177.43
      82 3175.35      88 3170.14    98.6 3159.89   107.6 3149.94   111.3 3148.43
   115.5 3148.32     124 3148.46   127.2 3149.71   132.5 3151.03     157 3151.39
   162.2 3153.74   166.4 3154.84   183.4 3155.27   199.6  3154.2   219.6 3157.14
   230.8 3157.81   251.7 3158.02   259.7 3157.04   267.7 3158.86   283.7 3157.85
   319.1 3159.58   334.5 3161.94   343.8 3162.55   363.8 3167.21372.5366 3170.22
#Mann= 5 ,-1,0
       0      .1       0   107.6    .045       0   127.2      .1       0
     180     .06       0  372.54      .1       0
Bank Sta=107.6,127.2
XS Rating Curve= 0 ,0
Exp/Cntr(USF)=0,0
Exp/Cntr=0.3,0.1

Type RM Length L Ch R = 1 ,6481    ,354.2,356.6,354.6
XS GIS Cut Line= 4
2342383.00495687578339.3803644722342342.17112983578310.299678693
2342263.60991771578305.2425069492342060.68542933 578305.80775622
#Sta/Elev= 30
       0 3189.07    23.1 3180.29    35.2 3174.48    45.2 3168.12    72.2 3147.97
    80.2 3144.12    84.2 3143.38   100.2 3144.12   108.2 3142.23   112.3 3141.93
   120.3  3143.5   128.2 3143.69   136.4 3143.24     1423142.162   148.3 3141.22
   152.4 3141.23   157.33142.227   164.3 3145.13   172.3  3146.6   180.5 3147.36
     204 3147.52   216.3 3146.36   224.3 3147.92   228.3 3148.06   260.3 3146.89
   276.8 3147.51   292.3  3149.8   304.3 3152.22   316.3 3155.47   331.8 3158.24
#Mann= 5 ,-1,0
       0      .1       0     110     .06       0     142    .045       0
   157.3     .06       0  201.56      .1       0
Bank Sta=142,157.3
XS Rating Curve= 0 ,0
Exp/Cntr(USF)=0,0
Exp/Cntr=0.3,0.1

Type RM Length L Ch R = 1 ,6125    ,240.5,245.4,250.3
XS GIS Cut Line= 3
2342486.31813058578002.2688975592342339.91856933577979.093677438
 2342016.0307369577979.093677438
#Sta/Elev= 30
       0 3175.79    18.4 3167.14    34.6 3160.64    58.9 3148.47    83.2 3141.13
   115.6 3138.46   148.2 3138.34     172 3136.44     184 3133.85     196 3128.83
     200 3127.54     204 3127.41     212 3127.58     216 3128.95     232 3135.02
     244 3136.28     292 3137.08     308 3136.65     316 3135.66     324 3133.36
     332 3132.85     336 3133.79     348 3139.26     364 3143.33     392 3152.23
     408 3158.38     428 3163.99     440  3169.2     448  3171.3472.1104 3182.32
#Mann= 5 ,-1,0
       0      .1       0      20     .06       0     196    .045       0
     216     .06       0  318.22      .1       0
Bank Sta=196,216
XS Rating Curve= 0 ,0
Exp/Cntr(USF)=0,0
Exp/Cntr=0.3,0.1

Type RM Length L Ch R = 1 ,5879    ,273.2,276.2,278.4
XS GIS Cut Line= 3
2342529.94872332577842.080820817  2342276.214606577732.799295042
2342047.60267852577727.146802329
#Sta/Elev= 30
       0 3159.73    10.6 3153.98    41.6  3141.3    54.2  3134.7    71.6 3131.28
    93.4 3124.96   115.2 3123.39   128.2 3124.55   163.1 3124.94   197.9 3123.43
     211 3123.92   233.4 3122.89   251.7 3120.95   263.2 3120.33   265.2 3120.97
     272 3124.71   288.3 3124.25   304.3  3122.3   312.3  3122.6   320.3 3124.62
   328.3 3124.98   340.3 3130.45   348.3 3131.64   384.3 3130.26   392.3 3133.08
   400.3 3134.39   420.4 3139.84   448.4 3148.96   476.4 3158.83504.9488  3170.7
#Mann= 6 ,-1,0
       0     .06       0     180      .1       0   251.7    .045       0
   265.2      .1       0  286.27     .06       0  386.27      .1       0
#XS Ineff= 2 , 0
          164.28  3129.2  277.08         3132.73
Permanent Ineff=
       F       F
Bank Sta=251.7,265.2
XS Rating Curve= 0 ,0
Exp/Cntr(USF)=0,0
Exp/Cntr=0.3,0.1

Type RM Length L Ch R = 1 ,5603    ,275.6,264,251.2
BEGIN DESCRIPTION:
The IFA is very tricky here
END DESCRIPTION:
XS GIS Cut Line= 3
2342581.44921248577619.1213860462342372.30698211577463.991863825
2342092.82262022 577475.29684925
#Sta/Elev= 30
       0 3135.01    46.4 3122.05    71.3 3119.83    81.3 3117.61    97.3 3117.89
   119.5 3115.06     151 3112.84   184.5 3113.12   195.8 3111.55   208.9 3111.52
   215.7 3112.36   248.2 3112.38   260.5 3114.39   272.5    3113   284.5 3113.33
   296.6 3109.27   336.6 3112.77   360.6 3111.51   368.6 3107.62   372.6 3107.09
   384.8 3109.04   392.6 3111.58   412.7 3113.02   428.7 3123.41   436.7 3126.28
   460.7  3126.7   488.8 3124.46   496.4    3128   512.7  3137.7540.1081 3144.74
#Mann= 6 ,-1,0
       0     .06       0    81.3      .1       0   195.8    .045       0
   208.9      .1       0   360.6     .06       0   460.7      .1       0
#XS Ineff= 2 , 0
                          260.13         3119.79
Permanent Ineff=
       F       F
Bank Sta=195.8,208.9
XS Rating Curve= 0 ,0
Exp/Cntr(USF)=0,0
Exp/Cntr=0.3,0.1

Type RM Length L Ch R = 1 ,5339    ,354.6,350.9,340.7
XS GIS Cut Line= 3
2342713.96876385577222.1907866792342434.85686193577288.446463824
2342098.23188718577339.198887471
#Sta/Elev= 30
       0 3137.46    47.1 3127.59    55.3 3124.23    73.7 3112.94    88.2  3106.8
   121.1 3107.15   134.2 3102.84   166.3 3105.27   207.4 3103.95   220.23101.814
   232.1 3101.21   240.83101.652   256.7 3102.12   273.2 3106.32   281.4 3107.25
   321.9 3106.03   370.5 3107.24   398.8 3104.47   409.4 3102.05   425.9 3101.36
   463.5 3105.26   471.6 3104.37   493.8 3105.57   524.2 3105.18   536.9 3109.51
   552.5 3118.53   560.5 3121.55   584.9 3122.15   613.2    3120   627.3 3129.18
#Mann= 5 ,-1,0
       0      .1       0   220.2    .045       0   240.8      .1       0
  567.81     .06       0  577.81      .1       0
#XS Ineff= 2 , 0
          163.27 3110.85  362.79         3109.73
Permanent Ineff=
       F       F
Bank Sta=220.2,240.8
XS Rating Curve= 0 ,0
Exp/Cntr(USF)=0,0
Exp/Cntr=0.3,0.1

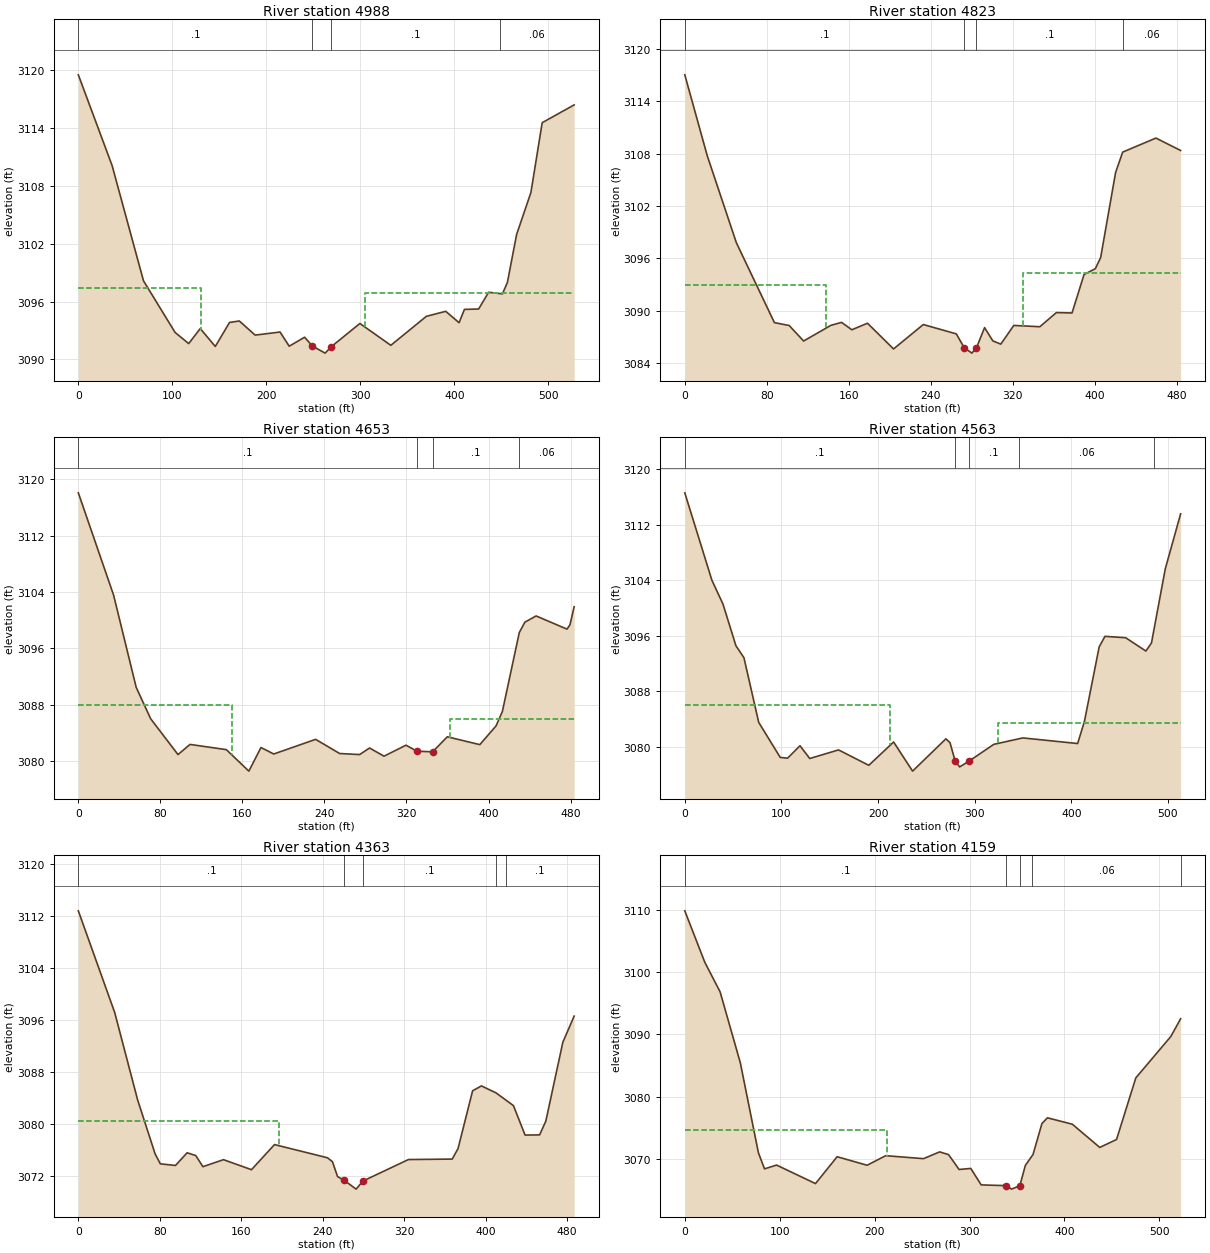
Type RM Length L Ch R = 1 ,4988    ,165.1,165.2,163.3
XS GIS Cut Line= 4
2342493.62234599576852.645754917 2342342.0918063576994.270896907
2342313.95636471 577013.712893942342087.78209199577188.387571372
#Sta/Elev= 30
       0 3119.55    35.9 3110.14    69.3 3098.17   102.9 3092.81   117.4 3091.65
   129.7 3093.21   145.7 3091.35   160.8 3093.84   171.2    3094   188.1 3092.53
   214.6 3092.85   224.3 3091.38   240.7 3092.31   248.9  3091.4   262.5 3090.66
   269.1 3091.33   299.5 3093.74   332.4 3091.47   370.2 3094.48   390.8    3095
     405 3093.82   410.7  3095.2   425.8 3095.24   436.4 3096.98   451.1 3096.81
   456.4    3098   466.2 3102.98   481.4 3107.33   493.4 3114.58   527.4 3116.43
#Mann= 4 ,-1,0
       0      .1       0   248.9    .045       0   269.1      .1       0
     448     .06       0
#XS Ineff= 2 , 0
          130.56 3097.39  304.98         3096.87
Permanent Ineff=
       F       F
Bank Sta=248.9,269.1
XS Rating Curve= 0 ,0
Exp/Cntr(USF)=0,0
Exp/Cntr=0.3,0.1

Type RM Length L Ch R = 1 ,4823    ,171.8,170,166.9
XS GIS Cut Line= 3
2342380.12363185576770.4264379812342108.46773509576984.491284624
2342006.32511791577076.854289521
#Sta/Elev= 30
       0 3117.05    21.9 3107.76    50.3 3097.78    87.4 3088.61   101.8 3088.28
   115.9  3086.5   142.5  3088.3   152.9 3088.64   162.9 3087.79   178.2 3088.54
   203.6 3085.59   232.6 3088.39   264.8 3087.32   272.5 3085.74     280 3085.11
   284.5 3085.73   292.4 3088.04   300.4 3086.52   308.2 3086.14   320.9 3088.29
   346.3 3088.14   362.4 3089.76   377.7 3089.72   389.4 3094.13   400.4  3094.8
   405.6 3096.07   420.2 3105.85   427.1 3108.18   459.5 3109.79   483.6 3108.37
#Mann= 4 ,-1,0
       0      .1       0   272.5    .045       0   284.5      .1       0
   427.1     .06       0
#XS Ineff= 2 , 0
          137.87 3092.94  329.73          3094.3
Permanent Ineff=
       F       F
Bank Sta=272.5,284.5
XS Rating Curve= 0 ,0
Exp/Cntr(USF)=0,0
Exp/Cntr=0.3,0.1

Type RM Length L Ch R = 1 ,4653    ,89.1,89.8,87.7
XS GIS Cut Line= 2
2342250.81542499576616.1258886242341919.39523095576968.191930819
#Sta/Elev= 30
       0 3118.06    34.4 3103.54    56.4 3090.47    70.5 3086.01    97.2 3080.92
   108.9 3082.36   144.3 3081.62   166.3 3078.57   178.1 3081.92   190.6    3081
   231.4 3083.08   254.8 3081.07   274.3 3080.92     284 3081.85   298.1 3080.69
   319.5 3082.25   330.23081.399  345.48 3081.31   359.8 3083.44   391.5 3082.33
   407.3 3084.98   413.5 3087.03   429.9 3098.16   429.9 3098.18   429.9  3098.2
   435.4  3099.7   446.4 3100.59   476.5 3098.72   479.4 3099.33   483.5  3101.9
#Mann= 4 ,-1,0
       0      .1       0   330.2    .045       0  345.48      .1       0
   429.9     .06       0
#XS Ineff= 2 , 0
           149.5 3087.94   362.7         3086.01
Permanent Ineff=
       F       F
Bank Sta=330.2,345.48
XS Rating Curve= 0 ,0
Exp/Cntr(USF)=0,0
Exp/Cntr=0.3,0.1

Type RM Length L Ch R = 1 ,4563    ,196.3,200.4,197.7
XS GIS Cut Line= 3
2342186.01928685576551.588661202 2341984.4214672576807.462816913
 2341860.3612705576947.805914439
#Sta/Elev= 30
       0 3116.61    28.1 3103.98    39.5 3100.57    52.9 3094.56    61.2 3092.83
    76.5  3083.5    98.8 3078.44   106.4 3078.34   119.2 3080.13   129.3 3078.29
   159.1 3079.53   190.4 3077.31   216.1 3080.67   235.7 3076.47   270.2 3081.13
   274.4 3080.58  279.85  3077.9   284.4 3077.08   293.8 3077.88   319.7 3080.33
   349.8 3081.26   406.5 3080.45   413.5 3083.62   428.8  3094.4   434.8 3095.91
   456.2 3095.71   477.1 3093.79   482.9 3094.95   497.2 3105.65513.0659 3113.58
#Mann= 5 ,-1,0
       0      .1       0  279.85    .045       0   293.8      .1       0
  345.75     .06       0  485.75      .1       0
#XS Ineff= 2 , 0
          212.29 3085.98  324.51         3083.44
Permanent Ineff=
       F       F
Bank Sta=279.85,293.8
XS Rating Curve= 0 ,0
Exp/Cntr(USF)=0,0
Exp/Cntr=0.3,0.1

Type RM Length L Ch R = 1 ,4363    ,204.2,204.1,196.9
XS GIS Cut Line= 2
2342020.86414999576448.4636226892341731.64881641576840.028618549
#Sta/Elev= 30
       0 3112.74    35.7 3097.11    58.2 3083.68    75.4 3075.36    80.5 3073.84
    95.4 3073.59   106.8 3075.54   115.3 3075.11   122.3  3073.4   142.5 3074.48
     170 3072.94   192.6  3076.8   244.6 3074.77   249.5 3074.17   254.5 3071.88
   261.3 3071.28   272.7 3069.95   279.4 3071.19   324.1  3074.5   367.1 3074.57
   372.8 3076.19   387.1 3085.07   395.7 3085.82     410 3084.76   427.2 3082.79
   438.6 3078.26   452.9 3078.29     459 3080.42   475.7 3092.54486.7943 3096.55
#Mann= 5 ,-1,0
       0      .1       0   261.3    .045       0   279.4      .1       0
     410     .06       0     420      .1       0
#XS Ineff= 2 , 0
           196.9  3080.5
Permanent Ineff=
       F       F
Bank Sta=261.3,279.4
XS Rating Curve= 0 ,0
Exp/Cntr(USF)=0,0
Exp/Cntr=0.3,0.1

Type RM Length L Ch R = 1 ,4159    ,392.1,392.3,382.9
XS GIS Cut Line= 3
2341896.97913679576360.2713995272341729.49787123576567.296852784
2341596.13315977576785.952949482
#Sta/Elev= 30
       0 3109.87    21.1 3101.59    37.2 3096.84    58.5 3085.43    77.6 3070.93
      84 3068.37    96.7 3068.98   137.7    3066   160.5 3070.32   192.1 3068.95
   211.7 3070.49   251.5 3070.01   268.5  3071.1   277.9 3070.66     289 3068.27
   301.3 3068.44   312.3 3065.79   338.8 3065.67   344.3 3065.11     353 3065.66
   358.8 3068.92   366.9 3070.68   376.3 3075.66   382.1 3076.58   408.3 3075.55
   437.2 3071.82   454.9 3073.09   475.2    3083   512.1 3089.66522.4068 3092.51
#Mann= 5 ,-1,0
       0      .1       0   338.8    .045       0     353      .1       0
  366.29     .06       0  522.41      .1       0
#XS Ineff= 2 , 0
          212.62 3074.64
Permanent Ineff=
       F       F
Bank Sta=338.8,353
XS Rating Curve= 0 ,0
Exp/Cntr(USF)=0,0
Exp/Cntr=0.3,0.1