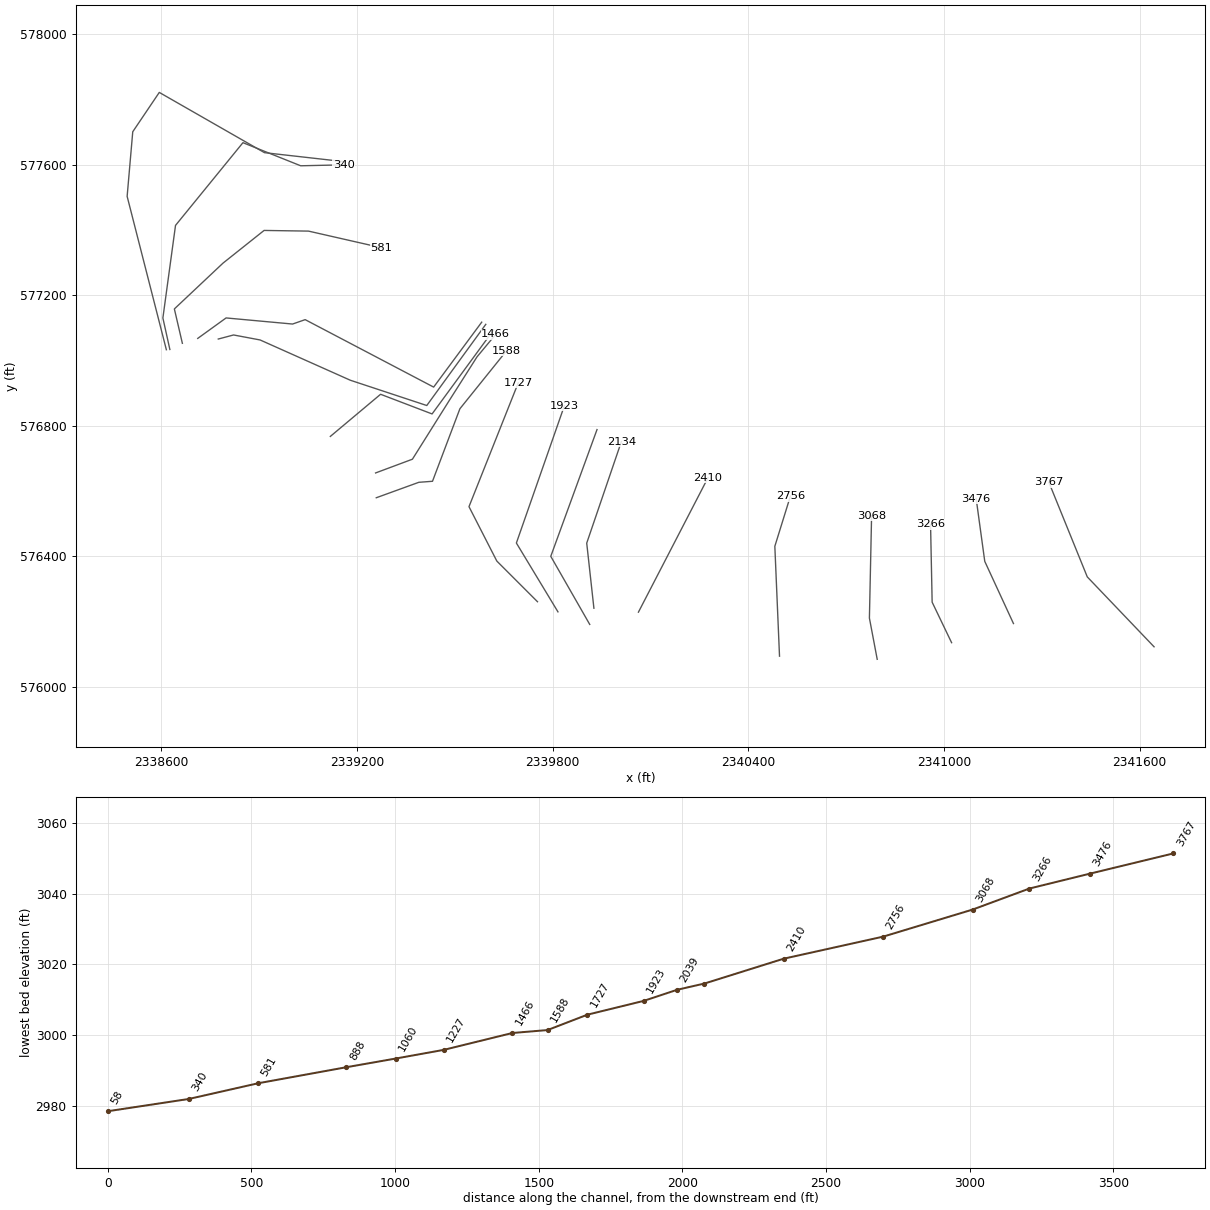
HEC-RAS study POCARN.prj: POCARN

--- POCARN.g01 (geometry) --- (continued)

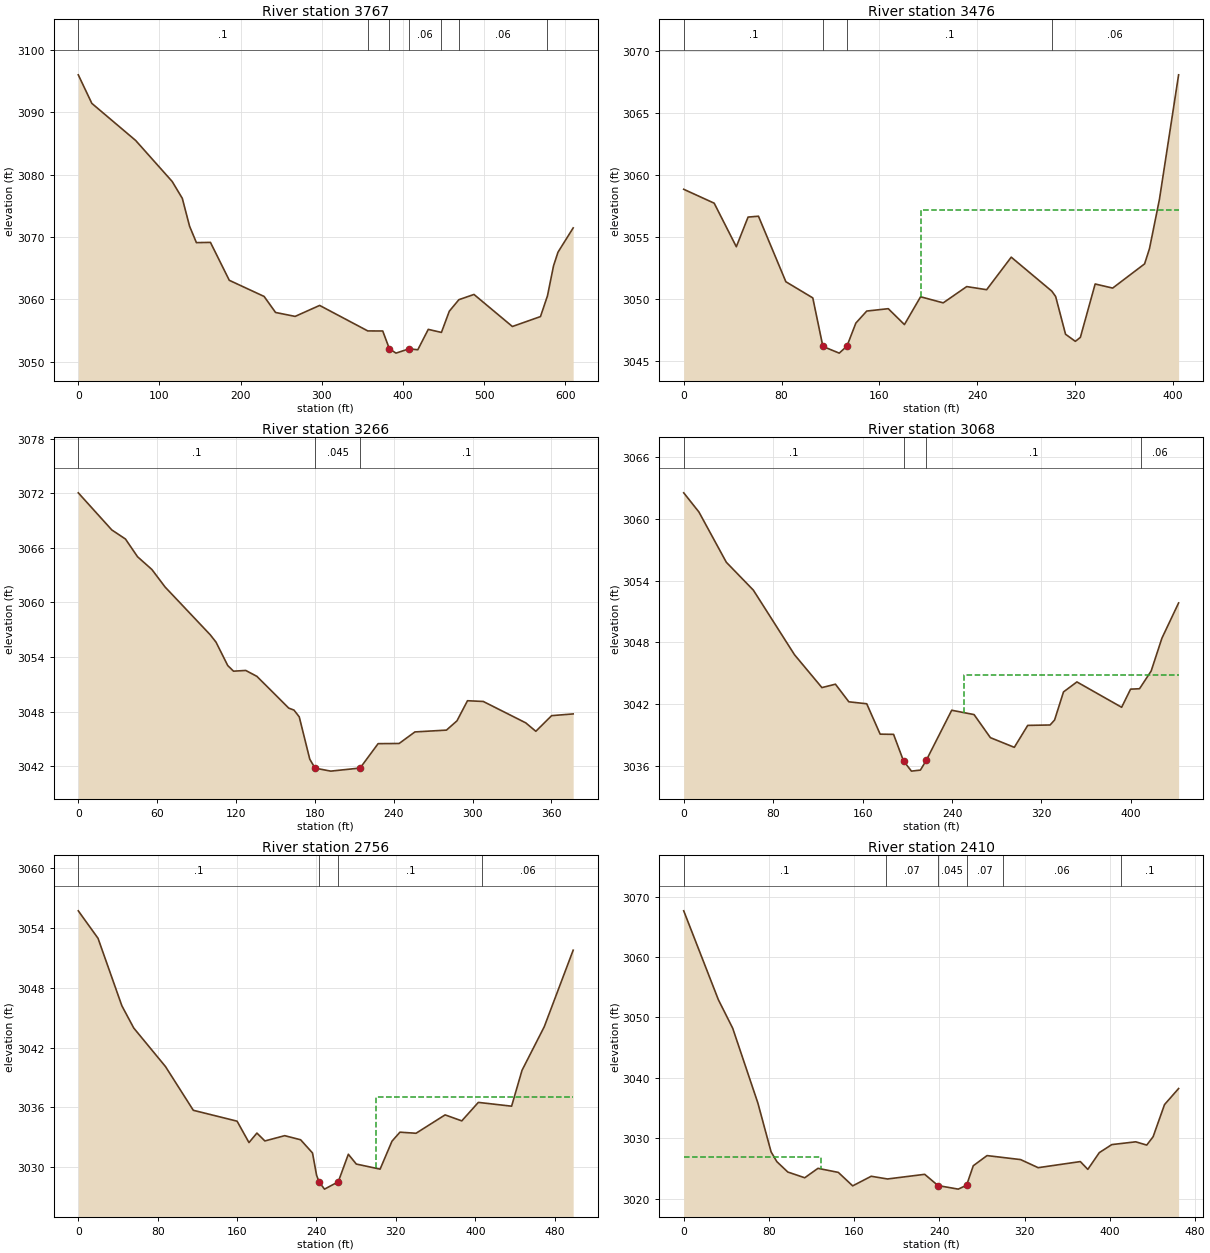
Type RM Length L Ch R = 1 ,3767    ,290.6,291.1,289.6
XS GIS Cut Line= 3
 2341644.6671179 576122.06116933 2341439.8146326576336.486200677
2341322.07231628576626.534345759
#Sta/Elev= 30
       0 3096.02    16.7 3091.44    70.7 3085.49   115.7 3078.91   128.1 3076.22
   137.1 3071.74   145.5 3069.11   162.8 3069.15     186 3063.07   228.9 3060.48
     243 3057.91   267.1 3057.28   297.3 3059.04   356.6 3054.95     375 3054.94
  383.16  3052.1   391.3 3051.39   407.5 3052.08   418.2 3051.93   431.1  3055.2
   447.3 3054.71     457 3058.11   468.8 3059.96   487.4  3060.8   534.7 3055.66
   569.3 3057.25   577.9 3060.56   585.4 3065.39   590.9 3067.58609.5867 3071.47
#Mann= 7 ,-1,0
       0      .1       0   356.6     .06       0  383.16    .045       0
   407.5     .06       0   447.3      .1       0   468.8     .06       0
   577.9      .1       0
Bank Sta=383.16,407.5
XS Rating Curve= 0 ,0
Exp/Cntr(USF)=0,0
Exp/Cntr=0.3,0.1

Type RM Length L Ch R = 1 ,3476    ,213.6,210.1,201.3
XS GIS Cut Line= 3
2341213.44405553576193.3888555132341125.42754498576384.091295035
2341099.02259181576576.749657014
#Sta/Elev= 30
       0 3058.85    24.9 3057.73      43 3054.22    52.6 3056.61    61.1 3056.68
    83.5  3051.4   105.5  3050.1  113.75 3046.19   127.1 3045.65   133.4 3046.21
   140.7 3048.07   149.6 3049.04   167.2 3049.23   180.4 3047.95   193.6 3050.19
   212.1  3049.7   231.3 3051.01   247.6 3050.76   267.7 3053.38   300.9 3050.64
     304 3050.21   312.1 3047.17   320.1  3046.6   324.2 3046.92   336.3 3051.22
   350.6 3050.89   376.7 3052.84   380.7 3054.07   388.8 3058.02   404.5 3068.07
#Mann= 4 ,-1,0
       0      .1       0  113.75    .045       0   133.4      .1       0
   300.9     .06       0
#XS Ineff= 2 , 0
                          194.35         3057.22
Permanent Ineff=
       F       F
Bank Sta=113.75,133.4
XS Rating Curve= 0 ,0
Exp/Cntr(USF)=0,0
Exp/Cntr=0.3,0.1

Type RM Length L Ch R = 1 ,3266    ,194.2,197.5,196.5
XS GIS Cut Line= 3
2341023.71957723576134.7111818142340964.06394231 576258.91225781
2340959.17413617 576497.53479752
#Sta/Elev= 30
       0 3072.05    25.5 3067.97    35.9 3066.97    45.1 3065.02      56 3063.62
      66  3061.7   100.4 3056.44   104.8 3055.63   113.7 3053.06   118.1 3052.44
   127.4 3052.52   135.9 3051.87   160.1 3048.38   164.1 3048.16   168.1 3047.42
   176.1 3042.77   180.1 3041.78   192.1 3041.45   214.4 3041.79   228.1 3044.47
   244.1 3044.49   256.1 3045.76   280.1 3045.96   288.1 3046.98   296.1 3049.19
   308.1 3049.11   340.4 3046.76   348.1 3045.83   360.1 3047.55   376.5 3047.74
#Mann= 3 ,0,0
       0      .1       0   180.1    .045       0   214.4      .1       0
Bank Sta=180.1,214.4
XS Rating Curve= 0 ,0
Exp/Cntr(USF)=0,0
Exp/Cntr=0.3,0.1

Type RM Length L Ch R = 1 ,3068    ,307.5,311.8,310.4
XS GIS Cut Line= 3
2340795.58228395 576083.770985162340771.65091885576210.128592919
2340778.35170108576524.108103106
#Sta/Elev= 30
       0 3062.52    13.6 3060.66    38.1 3055.78    62.3 3053.07    99.1  3046.8
   123.6 3043.61   135.7 3043.94   147.7 3042.23   163.7 3042.04   175.7 3039.09
   187.7 3039.07   196.6 3036.49   203.7  3035.5   211.7  3035.6     217 3036.56
   239.7 3041.41   259.7 3040.99   274.3 3038.75   295.7 3037.81   307.7 3039.94
   327.7 3039.98   331.7 3040.46   339.7 3043.19   351.7 3044.16   391.7  3041.7
   399.7 3043.46   407.7  3043.5   418.1 3045.22   427.7  3048.4442.6549 3051.83
#Mann= 4 ,-1,0
       0      .1       0   196.6    .045       0     217      .1       0
   408.6     .06       0
#XS Ineff= 2 , 0
                          250.83         3044.88
Permanent Ineff=
       F       F
Bank Sta=196.6,217
XS Rating Curve= 0 ,0
Exp/Cntr(USF)=0,0
Exp/Cntr=0.3,0.1

Type RM Length L Ch R = 1 ,2756    ,354.4,346.1,338.6
XS GIS Cut Line= 3
2340495.96159283576093.3435312032340481.60277376576430.297151892
2340529.46550398576584.415143172
#Sta/Elev= 30
       0 3055.68    19.9 3052.93    43.9 3046.18    55.9 3043.95    87.9 3040.09
   115.9 3035.72     160 3034.63     172 3032.49     180 3033.44     188 3032.65
     208 3033.18     224 3032.77     236 3031.45   240.1 3029.22   242.6 3028.55
   248.1 3027.83  261.93 3028.56   272.1 3031.32   280.1 3030.34   304.1 3029.83
   316.1 3032.63   324.1 3033.53   340.3 3033.42   369.6 3035.26   386.4 3034.66
   403.1 3036.51   436.6 3036.13   447.1 3039.72   469.5 3044.08498.6385 3051.74
#Mann= 4 ,-1,0
       0      .1       0   242.6    .045       0  261.93      .1       0
  407.26     .06       0
#XS Ineff= 2 , 0
                          299.83         3037.04
Permanent Ineff=
       F       F
Bank Sta=242.6,261.93
XS Rating Curve= 0 ,0
Exp/Cntr(USF)=0,0
Exp/Cntr=0.3,0.1

Type RM Length L Ch R = 1 ,2410    ,270.9,275.4,278.7
XS GIS Cut Line= 2
2340063.28251172576228.3164303992340276.75028846576640.893164822
#Sta/Elev= 30
       0 3067.65    32.5 3052.95      46 3048.21    69.6 3035.84      82 3027.76
    87.4 3026.14    97.7 3024.42   113.6 3023.47     126 3025.03   145.1 3024.36
   158.6 3022.13     176 3023.72   191.3 3023.27   226.2 3024.04   238.7 3022.18
   257.7 3021.59   265.5 3022.23   271.8 3025.46   284.7 3027.14   316.2 3026.48
   332.7 3025.14   372.3 3026.15   379.3 3024.86   390.1 3027.63   401.8 3028.96
   424.3 3029.42   434.6 3028.88   440.6 3030.26   451.3 3035.58464.5299 3038.24
#Mann= 6 ,-1,0
       0      .1       0     190     .07       0   238.7    .045       0
   265.5     .07       0     300     .06       0     410      .1       0
#XS Ineff= 2 , 0
          128.78 3026.96
Permanent Ineff=
       F       F
Bank Sta=238.7,265.5
XS Rating Curve= 0 ,0
Exp/Cntr(USF)=0,0
Exp/Cntr=0.3,0.1

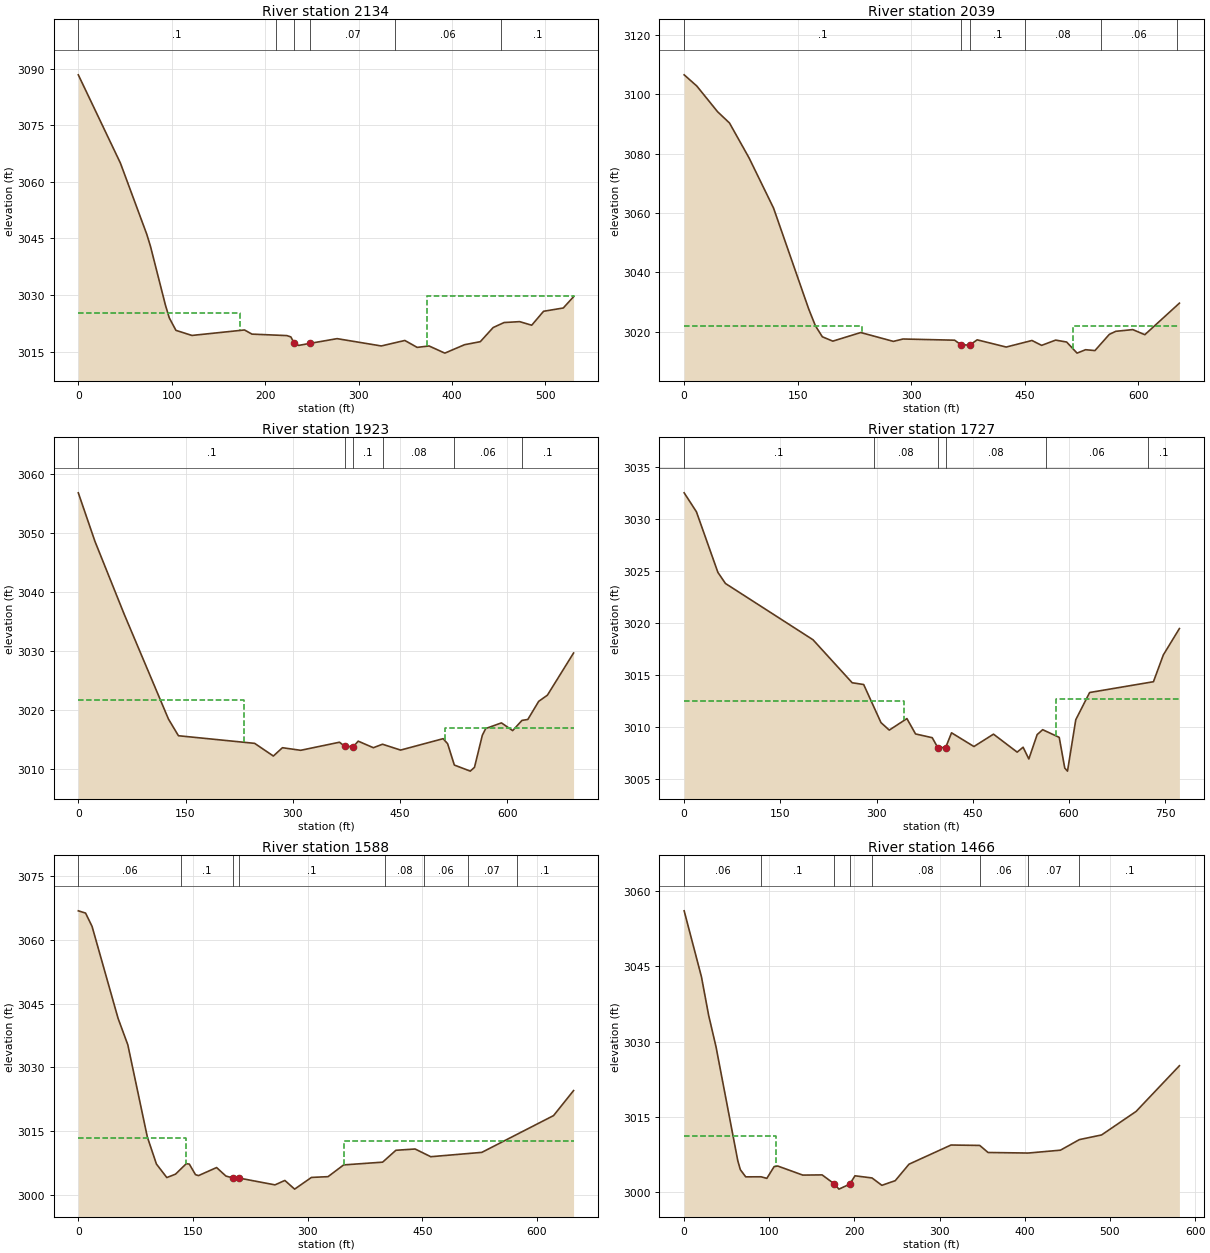
Type RM Length L Ch R = 1 ,2134    ,95.1,95.2,94
XS GIS Cut Line= 3
2339926.73008521576240.3531045472339904.67962373576440.040823478
2340011.06727361576751.612264651
#Sta/Elev= 30
       0 3088.37    45.1 3064.95    73.3 3046.08    77.3 3042.85    93.4 3027.17
    97.4 3023.91   104.5 3020.61   121.6 3019.26   177.9 3020.71   185.9 3019.61
   223.2 3019.22   227.5 3018.87   231.13017.218   235.9 3016.62   248.5 3017.18
     277 3018.41   324.3 3016.47   349.5 3017.93   362.7 3016.09   375.4 3016.47
   392.3 3014.57   413.4  3016.8   430.3 3017.61     444 3021.35   455.7 3022.68
   472.4 3022.92   485.3 3021.97     498 3025.67   519.1 3026.54   530.1 3029.53
#Mann= 6 ,-1,0
       0      .1       0   211.4     .07       0   231.1    .045       0
   248.5     .07       0   338.5     .06       0   452.5      .1       0
#XS Ineff= 2 , 0
          173.42 3025.34  373.52          3029.8
Permanent Ineff=
       F       F
Bank Sta=231.1,248.5
XS Rating Curve= 0 ,0
Exp/Cntr(USF)=0,0
Exp/Cntr=0.3,0.1

Type RM Length L Ch R = 1 ,2039    ,115.8,116.1,115.9
XS GIS Cut Line= 3
2339913.90746094576190.6959305212339794.41477372576399.479856546
2339936.23027065576788.159366631
#Sta/Elev= 30
       0  3106.6    16.7 3102.83    44.1 3094.18    59.9 3090.36    85.8 3078.58
   118.1 3061.69   164.5 3027.71   173.4 3022.01   182.6  3018.3   196.4 3016.84
   233.3 3019.74   276.4 3016.76   289.2 3017.56   357.3 3017.16   365.8 3015.61
   377.4 3015.52   387.1 3017.28   425.5 3014.85   459.5 3017.06   472.3 3015.42
   490.8 3017.19   505.3 3016.54   519.1  3012.8   530.3 3013.95   542.7 3013.66
   561.7 3019.12   570.2 3020.15   592.7 3020.73   608.6 3019.01654.3034 3029.64
#Mann= 6 ,-1,0
       0      .1       0   365.8    .045       0   377.4      .1       0
  450.56     .08       0  550.56     .06       0  650.56      .1       0
#XS Ineff= 2 , 0
           235.1 3021.79  513.86         3022.01
Permanent Ineff=
       F       F
Bank Sta=365.8,377.4
XS Rating Curve= 0 ,0
Exp/Cntr(USF)=0,0
Exp/Cntr=0.3,0.1

Type RM Length L Ch R = 1 ,1923    ,196.5,196.3,195.1
XS GIS Cut Line= 3
2339816.45469621576229.2462347822339688.94838293576440.320875015
2339836.26986652576861.608626338
#Sta/Elev= 30
       0 3056.85    23.3 3048.62    64.2 3036.27   126.1  3018.5   140.1 3015.66
   246.7 3014.37   272.9 3012.22   285.6 3013.63   311.1 3013.19   365.4 3014.56
  372.97 3013.85   384.8 3013.83   391.6 3014.74   412.8 3013.63   425.6 3014.22
   450.9 3013.23   510.4 3015.16   516.7 3014.31   526.1 3010.69   548.4 3009.66
   554.3 3010.31   565.3 3015.76     570 3016.88     592 3017.84   607.7 3016.53
   620.7 3018.26   628.9 3018.42   644.1 3021.49   656.3 3022.54   692.9 3029.69
#Mann= 6 ,-1,0
       0      .1       0  372.97    .045       0   384.8      .1       0
   425.6     .08       0   526.1     .06       0   620.7      .1       0
#XS Ineff= 2 , 0
           231.4 3021.66  512.45         3017.02
Permanent Ineff=
       F       F
Bank Sta=372.97,384.8
XS Rating Curve= 0 ,0
Exp/Cntr(USF)=0,0
Exp/Cntr=0.3,0.1

Type RM Length L Ch R = 1 ,1727    ,137,138.7,137.7
XS GIS Cut Line= 4
2339753.70847368576260.2905725292339628.96336065576385.035685563
 2339543.6114412576551.8002050932339694.61868329576931.287970007
#Sta/Elev= 30
       0 3032.55    19.1 3030.73    52.6 3024.89    64.4 3023.82   200.9  3018.4
     262 3014.26   279.9 3014.09   306.9 3010.42   319.8  3009.7   347.3 3010.81
   360.8 3009.33   386.8 3008.97   395.4 3008.02  407.72 3008.02   416.9 3009.44
   451.8 3008.12   482.3 3009.31   519.2 3007.58   528.5 3008.05   537.4 3006.92
   550.4 3009.27     559 3009.74   584.8    3009   593.4 3006.05   597.7 3005.75
   610.6  3010.7   632.2 3013.32   731.7 3014.36   747.1 3016.94772.1827 3019.48
#Mann= 6 ,-1,0
       0      .1       0  296.42     .08       0   395.4    .045       0
  407.72     .08       0  563.75     .06       0  723.75      .1       0
#XS Ineff= 2 , 0
          343.44  3012.5  580.12         3012.67
Permanent Ineff=
       F       F
Bank Sta=395.4,407.72
XS Rating Curve= 0 ,0
Exp/Cntr(USF)=0,0
Exp/Cntr=0.3,0.1

Type RM Length L Ch R = 1 ,1588    ,124.6,122.2,121.8
XS GIS Cut Line= 5
2339259.28112726576579.1603487872339389.79165014576626.515236985
2339431.70818718 576629.650888232339515.70890161576852.025767329
2339659.50203567577030.681466664
#Sta/Elev= 30
       0 3066.81     9.5 3066.28      18 3063.15      52 3041.56    64.8 3035.31
    90.3 3013.66   102.2  3007.3   115.8 3004.12   127.2 3004.92   141.2 3007.37
   145.2 3007.29   153.3  3004.8   157.3 3004.58   180.9 3006.47   193.2 3004.46
   202.6 3004.02   210.3    3004   257.3  3002.4   270.2 3003.44     283  3001.4
     305 3004.15   326.7 3004.33   347.1 3007.09   398.1 3007.74   415.5 3010.53
   440.6 3010.83   461.1 3009.02   527.9 3010.04   621.7 3018.68   647.9 3024.56
#Mann= 8 ,-1,0
       0     .06       0   134.1      .1       0   202.6    .045       0
   210.3      .1       0   401.3     .08       0     452     .06       0
   509.6     .07       0   573.3      .1       0
#XS Ineff= 2 , 0
          140.79 3013.37  347.86          3012.8
Permanent Ineff=
       F       F
Bank Sta=202.6,210.3
XS Rating Curve= 0 ,0
Exp/Cntr(USF)=0,0
Exp/Cntr=0.3,0.1

Type RM Length L Ch R = 1 ,1466    ,245.9,239.2,229.9
XS GIS Cut Line= 5
2339257.17565197576655.2191562242339370.13169527 576697.33835881
2339483.08773857576877.3022244052339568.28339835577011.317868998
2339625.70697312577080.339267739
#Sta/Elev= 30
       0  3056.1    20.3 3042.95    28.8 3035.23    37.4 3028.99      63 3006.23
      66 3004.45    72.3 3003.02    90.3 3003.03    97.1 3002.72   105.7 3005.07
   109.9 3005.18   139.3 3003.37     162 3003.41   175.9 3001.67   181.8 3000.57
   194.5 3001.57   200.6 3003.23   220.6  3002.8   232.2 3001.33   247.9 3002.26
   264.1 3005.55   313.4 3009.37   347.1 3009.29   356.9 3007.88     404 3007.77
   441.9 3008.34   464.1 3010.45   490.2 3011.38   530.7 3016.07   581.6 3025.19
#Mann= 8 ,-1,0
       0     .06       0    90.3      .1       0   175.9    .045       0
   194.5      .1       0   220.6     .08       0   347.1     .06       0
     404     .07       0   464.1      .1       0
#XS Ineff= 2 , 0
          107.83 3011.08
Permanent Ineff=
       F       F
Bank Sta=175.9,194.5
XS Rating Curve= 0 ,0
Exp/Cntr(USF)=0,0
Exp/Cntr=0.3,0.1

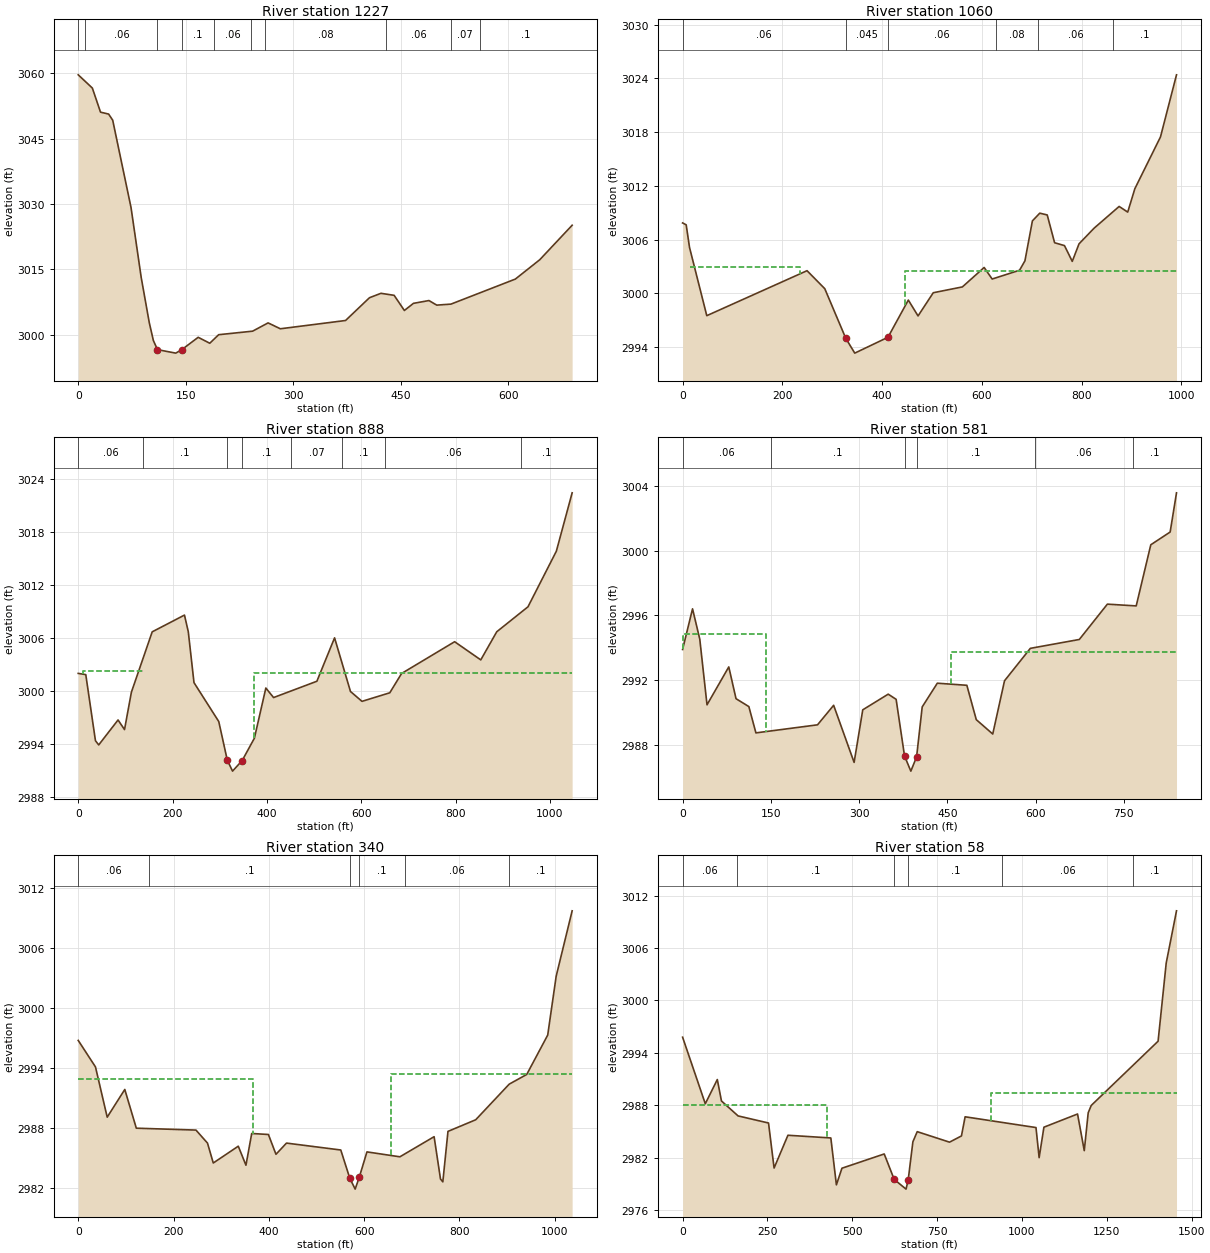
Type RM Length L Ch R = 1 ,1227    ,198.3,167,101.5
BEGIN DESCRIPTION:
xs 4
END DESCRIPTION:
XS GIS Cut Line= 4
2339118.37373436576767.2179449192339272.49172564 576896.44731649
2339430.43873534576836.1402764232339619.01789237577093.641764961
#Sta/Elev= 30
       0 3059.68    19.7 3056.64    31.1 3051.11    42.4 3050.67    48.1 3049.27
    73.7  3029.2    87.9 3013.14    99.2 3002.74   104.9 2998.67   110.6 2996.59
   136.1 2995.79   144.6 2996.59   167.4 2999.42   183.6 2998.06     196 3000.02
   243.4 3000.83     265 3002.73   282.1 3001.38   373.1 3003.28   406.5 3008.51
   422.5 3009.52   440.9 3009.06   455.2 3005.58   467.9 3007.22   489.5 3007.86
   500.4 3006.81   520.2 3007.04   610.1 3012.79   644.1 3017.22689.3663 3025.15
#Mann= 10 ,-1,0
       0      .1       0      10     .06       0   110.6    .045       0
   144.6      .1       0     190     .06       0  241.13      .1       0
  261.13     .08       0   430.2     .06       0   520.2     .07       0
   560.2      .1       0
Bank Sta=110.6,144.6
XS Rating Curve= 0 ,0
Exp/Cntr(USF)=0,0
Exp/Cntr=0.5,0.3

Type RM Length L Ch R = 1 ,1060    ,146.3,171.3,224.6
BEGIN DESCRIPTION:
xs 3
END DESCRIPTION:
XS GIS Cut Line= 6
2338774.71933144577065.8813814382338821.62480705577078.325691293
2338902.99144841577063.0096176262339179.63802903 576939.52377368
2339414.16540707576861.9861507382339595.08652727577110.872347837
#Sta/Elev= 30
       0 3007.87     7.2 3007.66    13.9 3005.13    48.5 2997.52   249.5 3002.54
   285.1 3000.53   327.2 2994.99   345.2 2993.34   411.8 2995.11   452.6 2999.26
   472.1 2997.49   502.6 3000.08     561 3000.73   604.6  3002.9   620.7 3001.61
   675.6 3002.59   686.4 3003.64   701.4  3008.1   716.2 3008.96   731.1 3008.76
   745.9 3005.66   765.7 3005.34   781.3 3003.58   794.9 3005.54     825 3007.28
   875.3 3009.71   892.5 3009.08   906.8 3011.69   958.2 3017.47990.3244  3024.4
#Mann= 6 ,-1,0
       0     .06       0   327.2    .045       0   411.8     .06       0
  628.05     .08       0  712.63     .06       0  862.63      .1       0
#XS Ineff= 3 ,-1
   15.77  234.93 3002.97  234.93   292.2 2995.59   446.8990.3244 3002.54
Permanent Ineff=
       F       F       F
Bank Sta=327.2,411.8
XS Rating Curve= 0 ,0
Exp/Cntr(USF)=0,0
Exp/Cntr=0.5,0.3

Type RM Length L Ch R = 1 ,888     ,300,307.1,314.5
BEGIN DESCRIPTION:
xs 2
END DESCRIPTION:
XS GIS Cut Line= 6
2338711.73197848577067.7958906472338798.67509988577130.543992421
2339002.54592725577111.8296024422339041.16851769577125.314268471
2339435.22500836576918.4641723872339582.64221741577117.573130067
#Sta/Elev= 30
       0 3001.97      16 3001.83    36.5 2994.34    43.4 2993.86    84.4 2996.69
    98.1  2995.6   112.7 2999.84   156.8 3006.68   225.2 3008.58   233.3 3006.69
   245.4 3000.92   297.9 2996.51     3162992.126   327.1 2990.89   347.52992.087
   373.4 2994.62   397.7 3000.31   414.1 2999.23   505.9 3001.08   543.4    3006
   577.1 2999.92   601.5  2998.8   660.4 2999.77   685.5 3001.96   797.9 3005.56
   853.3  3003.5   887.2 3006.69   953.4 3009.52  1013.5 3015.82    1047 3022.44
#Mann= 8 ,-1,0
       0     .06       0  137.22      .1       0     316    .045       0
   347.5      .1       0  452.05     .07       0  559.88      .1       0
  651.33     .06       0  939.22      .1       0
#XS Ineff= 3 ,-1
   10.82  136.56 3002.27  136.56     290    2994   373.5    1047    3002
Permanent Ineff=
       F       F       F
Bank Sta=316,347.5
XS Rating Curve= 0 ,0
Exp/Cntr(USF)=0,0
Exp/Cntr=0.5,0.3

Type RM Length L Ch R = 1 ,581     ,234.6,241.7,240.9
XS GIS Cut Line= 6
2338664.57330325577052.7584464512338640.04582477577158.164792367
 2338789.0781505577298.494250266 2338915.2079854577398.881743966
2339051.42803193577396.8158314532339274.74874767577345.966597476
#Sta/Elev= 30
       0 2993.89    16.9 2996.41    29.2 2994.53    41.5 2990.46    78.5 2992.81
    90.8 2990.84   112.6 2990.35   124.6 2988.72   229.3 2989.22   256.7 2990.43
   291.5 2986.89   306.2 2990.15   349.4 2991.12   362.9  2990.8   377.22987.286
   387.9 2986.35  397.67 2987.23   407.2 2990.33   432.9  2991.8   483.1 2991.67
   499.1 2989.54   527.1 2988.65   547.1 2991.95     591 2993.96   674.2 2994.51
   721.9  2996.7   770.9 2996.59   795.7 3000.38   828.6 3001.17   839.4  3003.6
#Mann= 6 ,-1,0
       0     .06       0     150      .1       0   377.2    .045       0
  397.67      .1       0  599.09     .06       0  765.67      .1       0
#XS Ineff= 2 , 0
           141.2 2994.87  456.34         2993.73
Permanent Ineff=
       F       F
Bank Sta=377.2,397.67
XS Rating Curve= 0 ,0
Exp/Cntr(USF)=0,0
Exp/Cntr=0.3,0.1

Type RM Length L Ch R = 1 ,340     ,281.9,281.9,281.9
XS GIS Cut Line= 6
 2338626.2361811577033.8354169162338604.82854581577130.325002913
2338643.57545066577414.3220573782338850.34244517577667.994527499
2339027.43454696577597.1576867862339159.53568234577600.029450599
#Sta/Elev= 30
       0 2996.76    36.2 2994.11    60.8 2989.09    97.7 2991.86   121.9 2987.99
   247.1  2987.8   271.3  2986.5   283.4 2984.51   335.9 2986.19     352 2984.29
   364.1 2987.46   399.1 2987.36     415 2985.38   437.1  2986.5     551 2985.81
   569.8 2983.01   581.2  2981.9   589.8 2983.08   605.9 2985.62   675.1 2985.13
   746.9 2987.14   760.3 2982.91   765.2 2982.63     776 2987.67   834.2 2988.83
   904.5 2992.39   941.3 2993.36   985.3 2997.29  1003.1 3003.18  1036.6 3009.71
#Mann= 6 ,-1,0
       0     .06       0  148.84      .1       0   569.8    .045       0
   589.8      .1       0  685.46     .06       0   904.5      .1       0
#XS Ineff= 2 , 0
          366.78 2992.88  655.81         2993.39
Permanent Ineff=
       F       F
Bank Sta=569.8,589.8
XS Rating Curve= 0 ,0
Exp/Cntr(USF)=0,0
Exp/Cntr=0.3,0.1

Type RM Length L Ch R = 1 ,58      ,,,
XS GIS Cut Line= 6
2338615.48761906 577033.05140625  2338495.200987577503.346735572
2338512.43156988577701.4984386472338593.79821124 577822.11251878
2338916.39301287577637.3623801642339162.40744615577609.601996641
#Sta/Elev= 30
       0  2995.8    66.9 2988.19   102.3 2990.96   114.5 2988.51   163.5  2986.8
   253.2 2985.99   269.6 2980.84   310.4 2984.59   436.8 2984.28   453.2 2978.92
   469.5 2980.82   594.1 2982.45   623.62979.538   658.5 2978.43   664.92979.526
   678.6 2983.84   691.4    2985   786.6  2983.8   821.7 2984.51   832.5  2986.7
  1041.3 2985.47  1050.6 2982.03  1064.7 2985.51  1163.8 2987.02  1183.6 2982.83
  1195.2 2987.16  1204.2    2988  1401.1 2995.34  1425.1 3004.29  1455.4 3010.25
#Mann= 6 ,-1,0
       0     .06       0  160.62      .1       0   623.6    .045       0
   664.9      .1       0  942.47     .06       0 1326.51      .1       0
#XS Ineff= 2 , 0
          426.37 2988.02  908.62         2989.47
Permanent Ineff=
       F       F
Bank Sta=623.6,664.9
XS Rating Curve= 0 ,0
Exp/Cntr(USF)=0,0
Exp/Cntr=0.3,0.1
LCMann Table=0

Chan Stop Cuts=-1
Use User Specified Reach Order=0
Composite Channel Slope=5